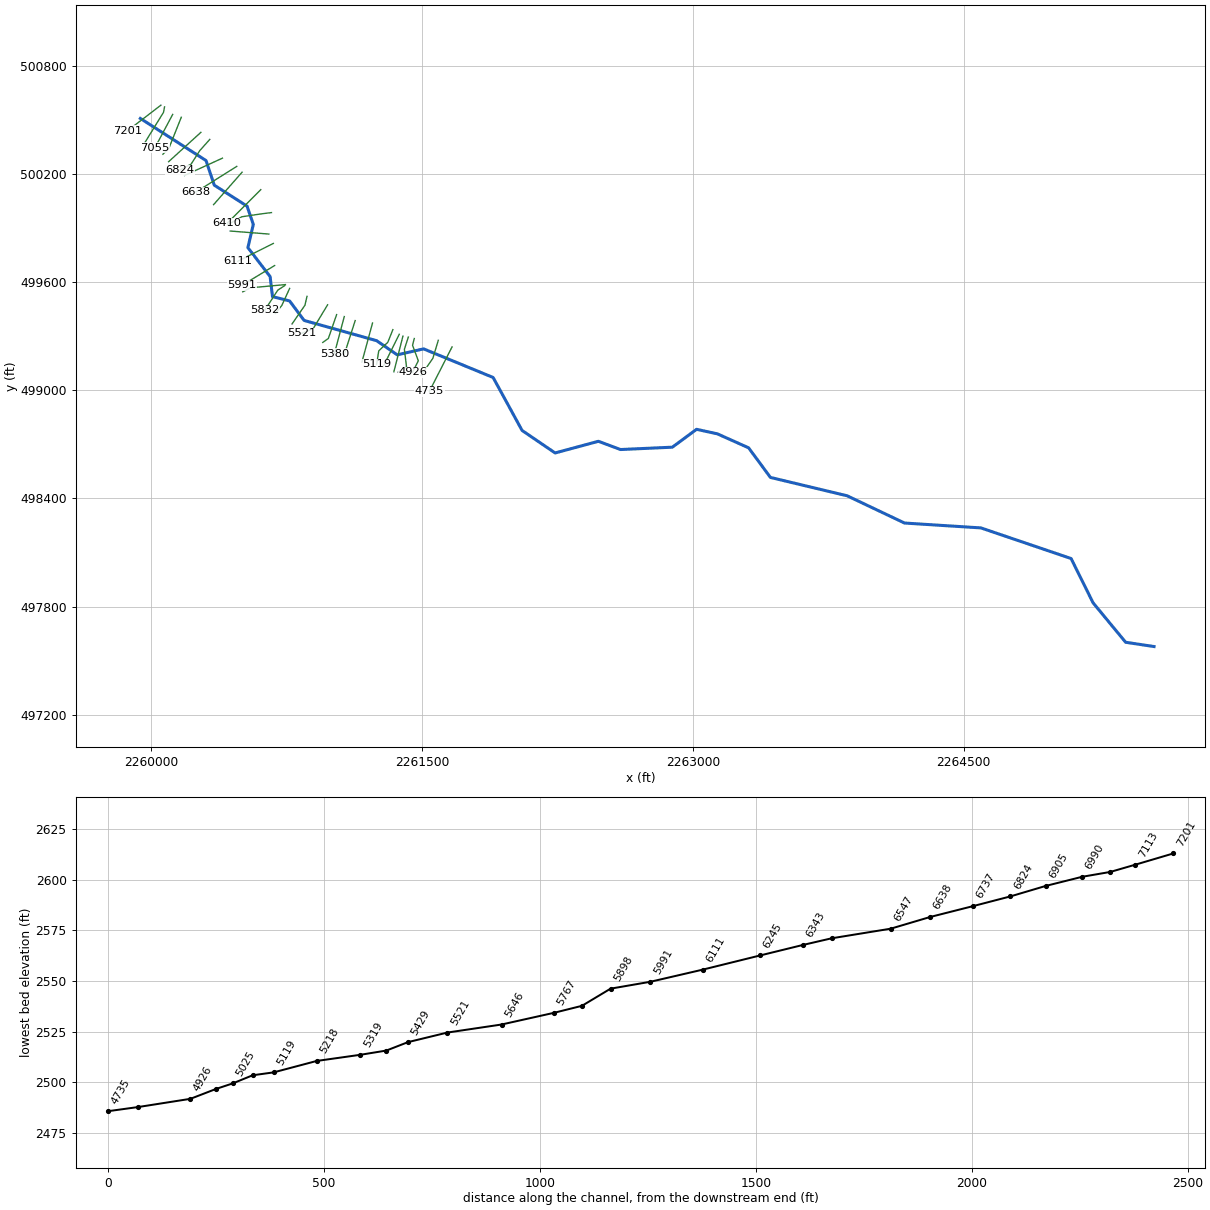
--- ELKLCKRN1.prj (project) ---

Proj Title=ELKLCKRN1
Current Plan=p01
Default Exp/Contr=0,0
English Units
Geom File=g01
Flow File=f01
Plan File=p01
Background Map Layer=Inundation Boundary (01pct Value_0)
BEGIN DESCRIPTION:
----------MODEL BY WOOD PLC 2021----------
Stream Name: Elklick Run I
Flood Zone: Enhanced Approximate
Pocahontas County, WV
HEC-RAS Version: RAS 6.1
Vertical Datum: NAVD88
Projection: NAD 1983 StatePlane West Virginia S FIPS 4702 (US Feet)
Terrain: 1-meter LIDAR (FEMA Region III 3DEP collected 2016-2018)
Land Use: 2019 NLCD
Hydrologic Method:
WV SIR2010-5033 regression equations
END DESCRIPTION:
DSS Export Rating Curves= 0
DSS Export Rating Curve Sorted= 0
DSS Export Volume Flow Curves= 0
DXF OffsetX= 0
DXF OffsetY= 0
DXF ScaleX= 0
DXF ScaleY= 0

--- ELKLCKRN1.p01 (plan) ---

Plan Title=Floodplain
Program Version=6.10
Short Identifier=Floodplain
Geom File=g01
Flow File=f01
Subcritical Flow
K Sum by GR= 0
Std Step Tol= 0.01
Critical Tol= 0.01
Num of Std Step Trials= 20
Max Error Tol= 0.3
Flow Tol Ratio= 0.001
Split Flow NTrial= 30
Split Flow Tol= 0.02
Split Flow Ratio= 0.02
Log Output Level= 0
Friction Slope Method= 1
Unsteady Friction Slope Method= 2
Unsteady Bridges Friction Slope Method= 1
Parabolic Critical Depth
Global Vel Dist= 0 , 0 , 0
Global Log Level= 0
CheckData=True
Encroach Param=-1 ,0,0, 0
Mapping Interval=1HOUR
Computation Time Step Use Courant=        0
Computation Time Step Use Time Series=    0
Computation Time Step Count To Double=0
Computation Time Step Max Doubling=0
Computation Time Step Max Halving=0
Computation Time Step Residence Courant=0
Run HTab= 0
Run UNet= 0
Run Sediment= 0
Run PostProcess= 0
Run WQNet= 0
Run RASMapper=-1
UNET Theta= 0
UNET Theta Warmup= 0
UNET ZTol= 0
UNET ZSATol= 0
UNET MxIter= 0
UNET Max Iter WO Improvement= 0
UNET MaxInSteps= 0
UNET DtIC= 0
UNET DtMin= 0
UNET MaxCRTS= 0
UNET WFStab= 0
UNET SFStab= 0
UNET WFX= 1
UNET SFX= 1
UNET Gravity=32.174
UNET 1D Methodology=Finite Difference
UNET DSS MLevel= 1
UNET Pardiso=0
UNET DZMax Abort= 0
UNET Use Existing IB Tables= 0
UNET Froude Reduction=False
UNET Froude Limit= 0
UNET Froude Power= 0
UNET D1 Cores= 0
UNET WindReference=Eulerian
UNET WindDragFormulation=Hsu (1988)
UNET D2 Coriolis=0
UNET D2 Cores= 0
UNET D2 Theta= 1
UNET D2 Theta Warmup= 1
UNET D2 Z Tol= 0.01
UNET D2 Volume Tol= 0.01
UNET D2 Max Iterations= 20
UNET D2 Equation= 0
UNET D2 RampUpFraction=0.1
UNET D2 TimeSlices= 1
UNET D2 Turbulence Formulation=Non-Conservative (original)
UNET D2 Eddy Viscosity=0.3
UNET D2 Transverse Eddy Viscosity=0.1
UNET D2 Smagorinsky Mixing=0
UNET D2 BCVolumeCheck=0
UNET D2 Cores=0
UNET D2 SolverType=PARDISO (Direct)
UNET D2 Minimum Iterations= 2147483647
UNET D2 Maximum Iterations= 2147483647
UNET D2 Restart Number= 10
UNET D2 Relaxation Coeff=1.3
UNET D2 SOR Precondition Iterations= 10
UNET D2 ILUT Maximum Fill= 8
UNET D2 ILUT Tolerance=1E-08
UNET D1D2 MaxIter= 0
UNET D1D2 ZTol=0.01
UNET D1D2 QTol=0.1
UNET D1D2 MinQTol=1
Write IC File= 0
Write IC File at Fixed DateTime=0
Write IC File at Sim End=0
Echo Input=False
Echo Parameters=False
Echo Output=False
Write Detailed= 0
HDF Write Warmup=0
HDF Write Time Slices=0
HDF Flush=0
HDF Compression= 1
HDF Chunk Size= 1
HDF Spatial Parts= 1
HDF Use Max Rows=0
HDF Fixed Rows= 1
Calibration Method= 0
Calibration Iterations= 20
Calibration Max Change=0.05
Calibration Tolerance=0.2
Calibration Maximum=1.5
Calibration Minimum=0.5
Calibration Optimization Method= 1
WQ AD Non Conservative
WQ ULTIMATE=-1
WQ Max Comp Step=1HOUR
WQ Output Interval=15MIN
WQ Output Selected Increments= 0
WQ Output face flow=0
WQ Output face velocity=0
WQ Output face area=0
WQ Output face dispersion=0
WQ Output cell volume=0
WQ Output cell surface area=0
WQ Output cell continuity=0
WQ Output cumulative cell continuity=0
WQ Output face conc=0
WQ Output face dconc_dx=0
WQ Output face courant=0
WQ Output face peclet=0
WQ Output face adv mass=0
WQ Output face disp mass=0
WQ Output cell mass=0
WQ Output cell source sink temp=0
WQ Output nsm pathways=0
WQ Output nsm derived pathways=0
WQ Create Restart=0
WQ Fixed Restart=0
WQ System Summary=0
WQ Write To DSS=0
Sorting and Armoring Iterations= 10
XS Update Threshold= 0.02
Bed Roughness Predictor= 0
Hydraulics Update Threshold= 0.02
Energy Slope Method= 1
Volume Change Method= 1
Sediment Retention Method= 0
Sediment TS Multiplier= 1
Warm Up Method= 0
XS Weighting Method= 0
Number of US Weighted Cross Sections= 1
Number of DS Weighted Cross Sections= 1
Upstream XS Weight=0
Main XS Weight=1
Downstream XS Weight=0
Number of DS XS's Weighted with US Boundary= 1
Upstream Boundary Weight= 1
Weight of XSs Associated with US Boundary= 0
Number of US XS's Weighted with DS Boundary= 1
Downstream Boundary Weight= 0.5
Weight of XSs Associated with DS Boundary= 0.5
Percentile Method= 0
Sediment Output Level= 3
Mass or Volume Output= 0
Output Increment Type= 1
Profile and TS Output Increment= 1
Transport Output Increment 1
XS Output Flag= 0
XS Output Increment= 10
Read HDF5 Sediment Hotstart= 0
Sediment Hotstart Type= 0
Write Gradation File= 0
Read Gradation Hotstart= 0
Write HDF5 File= 1
Write Binary Output= 1
Write DSS Sediment File= 0
DSS Sediment Output Type= 1
SV Curve= 0
Specific Gage Flag= 0
Subcell Erosion Methods= 0
Subcell Deposition Methods= 0
Advection Scheme= 1
Matrix Solver= 0
Implicit Weighting Factor= 1
Maximum Outer Loop Convergence Iterations= 5
Convergence Maximum Absolute= 0.001
Convergence RMSE= 0.0001
Grain Fractions Max Abs Error= 0.001
Max Subgrid Regions= 1
Max Subgrid Length Scale= 3.402823E+38
Initial Layer Thickness= 3.402823E+38
Min Layer Thickness= 3.402823E+38
Max Layer Thickness= 3.402823E+38
Number of Layers= 5

--- ELKLCKRN1.f01 (steady flow) ---

Flow Title=Flow
Program Version=6.10
Number of Profiles= 6
Profile Names=01pct,10pct,04pct,02pct,0_2pct,01plus
River Rch & RM=ELKLCKRN1,Main            ,7201
     586     310     412     496     819     867
River Rch & RM=ELKLCKRN1,Main            ,4062
     675     359     476     573     940     999
River Rch & RM=ELKLCKRN1,Main            ,2096
     779     416     551     661    1080    1150
Boundary for River Rch & Prof#=ELKLCKRN1,Main            , 1
Up Type= 0
Dn Type= 3
Dn Slope=0.02123
Boundary for River Rch & Prof#=ELKLCKRN1,Main            , 2
Up Type= 0
Dn Type= 3
Dn Slope=0.02123
Boundary for River Rch & Prof#=ELKLCKRN1,Main            , 3
Up Type= 0
Dn Type= 3
Dn Slope=0.02123
Boundary for River Rch & Prof#=ELKLCKRN1,Main            , 4
Up Type= 0
Dn Type= 3
Dn Slope=0.02123
Boundary for River Rch & Prof#=ELKLCKRN1,Main            , 5
Up Type= 0
Dn Type= 3
Dn Slope=0.02123
Boundary for River Rch & Prof#=ELKLCKRN1,Main            , 6
Up Type= 0
Dn Type= 3
Dn Slope=0.02123
DSS Import GetInterval= 0
DSS Import GetPeak= 0
DSS Import FillOption= 0

--- ELKLCKRN1.g01 (geometry) ---

Geom Title=Geometry
Program Version=6.10

River Reach=ELKLCKRN1       ,Main
Reach XY= 30
     2259939.466      500507.762     2260303.444      500273.959
     2260349.136      500137.558     2260530.638      500021.346
     2260565.268      499919.976     2260535.303      499791.062
     2260658.451      499630.6122260671.53796605499519.413393283
2260766.42726931  499495.2694238      2260846.79      499387.311
     2261248.143      499275.166     2261362.653      499196.549
2261508.69062981499229.610242056     2261893.943      499070.919
     2262054.327      498777.134      2262237.49      498652.265
     2262477.242      498717.012     2262599.631      498671.276
     2262886.935      498684.3152263021.21970476498783.413114294
2263136.44340953498758.330626457     2263309.446      498680.696
     2263430.353      498516.558     2263855.331      498414.694
     2264173.285      498263.581 2264596.3234238 498236.61311524
     2265096.105      498066.771     2265217.869       497821.13
     2265398.332      497602.236     2265555.804      497578.518

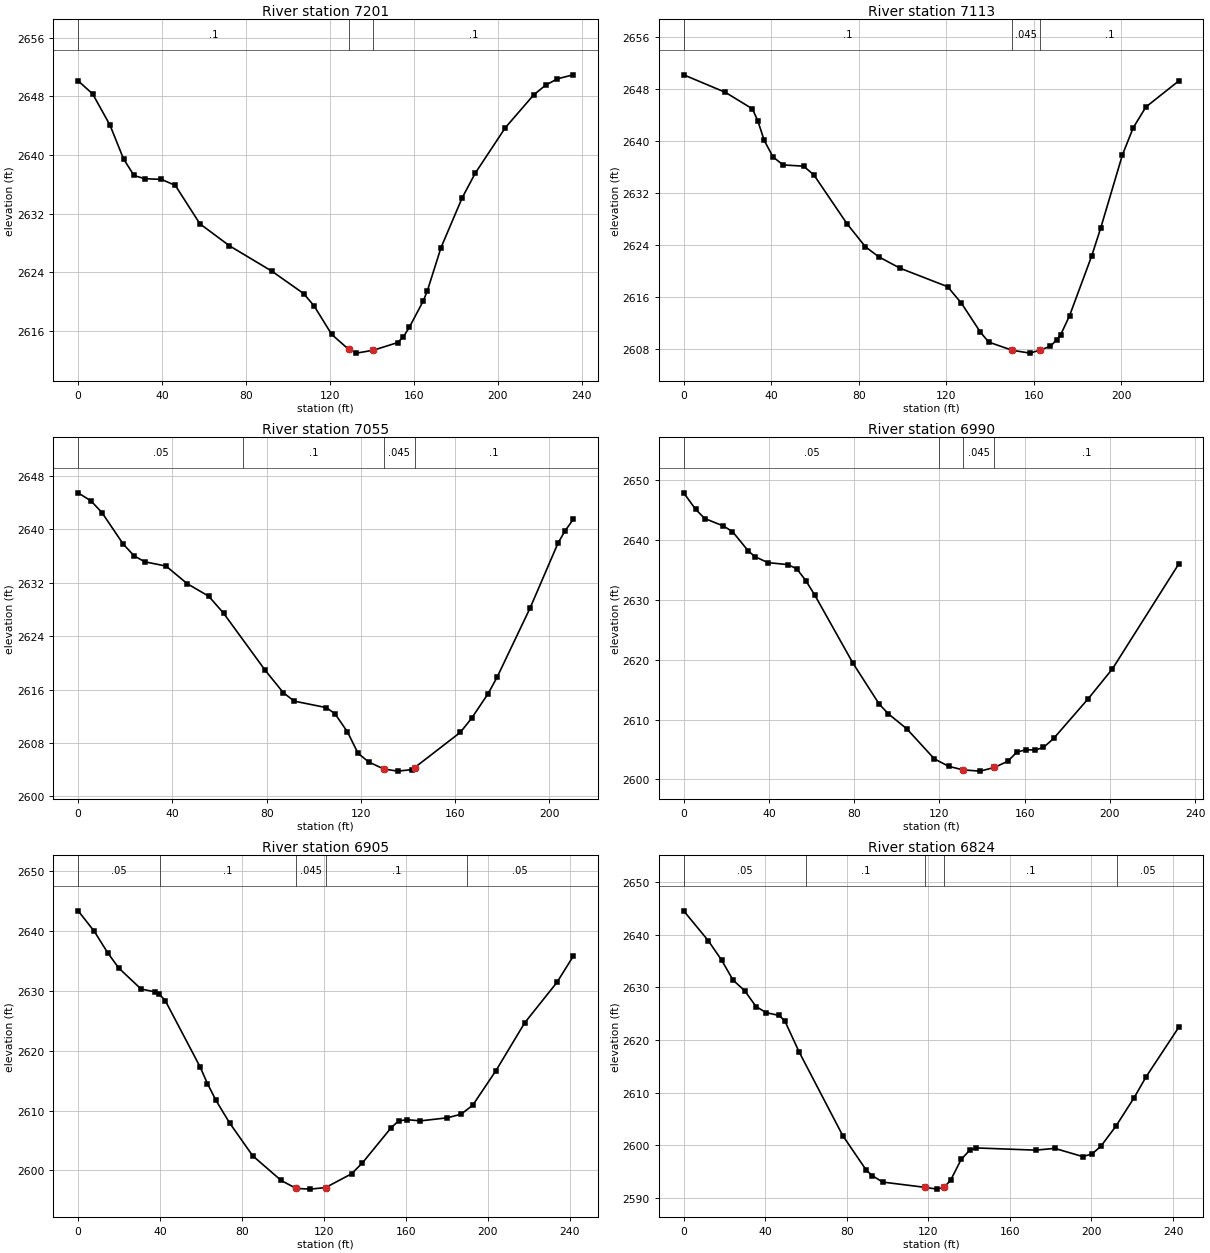
Type RM Length L Ch R = 1 ,7201    ,84,87.9,92.2
XS GIS Cut Line= 2
2260053.34123277500581.3586191322259866.28567449500437.705261549
#Sta/Elev= 30
       0 2650.13     6.9 2648.35    15.2 2644.06    21.6 2639.48    26.6  2637.2
    31.7 2636.76    39.7 2636.67    46.3 2635.84      58  2630.6    72.1 2627.59
    92.3 2624.12   107.4 2621.07   112.4 2619.38   120.8 2615.48   128.92613.431
   132.6 2612.92   140.7 2613.32   152.2 2614.36     155 2615.16   157.8 2616.45
   164.5 2620.09   166.4 2621.45   172.9 2627.35     183 2634.16   189.2 2637.51
   203.5 2643.72     217  2648.2   222.7 2649.54   228.4 2650.42   235.9 2650.96
#Mann= 3 ,-1,0
       0      .1       0   128.9    .045       0   140.7      .1       0
Bank Sta=128.9,140.7
XS Rating Curve= 0 ,0
Exp/Cntr(USF)=0,0
Exp/Cntr=0.3,0.1

Type RM Length L Ch R = 1 ,7113    ,57.5,58.2,58.9
XS GIS Cut Line= 3
2260073.50378306500571.9651003062260067.70759807500541.328122531
2259965.44633442500375.308824048
#Sta/Elev= 30
       0 2650.16    19.1 2647.46    31.4 2644.93    33.9 2643.07    36.8 2640.08
    40.8 2637.55    45.4 2636.31    54.8 2636.12    59.5 2634.77    74.6 2627.28
      83 2623.74    89.1 2622.19    98.9 2620.43   120.6 2617.59   126.9 2615.06
   135.6 2610.59   139.4 2609.07   150.1 2607.82   158.2 2607.38   162.9 2607.86
   167.6 2608.44   170.5 2609.46   172.3 2610.24   176.3 2613.12   186.4 2622.29
   190.5 2626.56   200.5 2637.89   205.4 2642.02   211.2 2645.22   226.2 2649.22
#Mann= 3 ,-1,0
       0      .1       0   150.1    .045       0   162.9      .1       0
Bank Sta=150.1,162.9
XS Rating Curve= 0 ,0
Exp/Cntr(USF)=0,0
Exp/Cntr=0.3,0.1

Type RM Length L Ch R = 1 ,7055    ,63.9,65,66.4
XS GIS Cut Line= 2
2260118.69193673500530.0643230892260019.88825001500344.652417916
#Sta/Elev= 30
       0 2645.45     5.5 2644.22    10.1 2642.49    19.1 2637.78    23.7 2636.03
    28.2 2635.13    37.3 2634.48    46.3 2631.84    55.4 2629.97    61.7 2627.43
    79.4 2618.86    87.1 2615.51    91.7 2614.26   105.3 2613.29     109 2612.37
   114.3 2609.64   118.8 2606.43   123.4 2605.13   129.7  2604.1   135.6 2603.78
   141.5    2604  142.812604.312   162.2 2609.59     167 2611.71     174  2615.4
   177.8 2617.85   191.8 2628.21   203.6 2637.89   206.5 2639.69   210.1 2641.47
#Mann= 4 ,-1,0
       0     .05       0      70      .1       0   129.7    .045       0
  142.81      .1       0
Bank Sta=129.7,142.81
XS Rating Curve= 0 ,0
Exp/Cntr(USF)=0,0
Exp/Cntr=0.3,0.1

Type RM Length L Ch R = 1 ,6990    ,90.5,84.7,79.5
XS GIS Cut Line= 3
2260166.24274281500514.4172636752260097.51654942500342.187766994
2260064.39549237 500309.06670994
#Sta/Elev= 30
       0 2647.85     5.6  2645.1     9.9 2643.56    18.6 2642.32    22.9 2641.38
    30.2  2638.2    33.3 2637.22    39.5  2636.2    48.8 2635.87      53 2635.19
    57.3 2633.21    61.6 2630.72    79.5 2619.37    91.8 2612.55    96.1 2610.94
   104.7 2608.45   117.6 2603.44   124.3  2602.2   131.12601.595   139.1 2601.39
   145.82602.004   152.1 2603.04   156.4 2604.59   160.7 2604.95     165 2604.92
   168.8 2605.34   173.6 2606.84   189.9 2613.51   201.2 2618.47   232.3 2635.97
#Mann= 4 ,-1,0
       0     .05       0     120      .1       0   131.1    .045       0
   145.8      .1       0
Bank Sta=131.1,145.8
XS Rating Curve= 0 ,0
Exp/Cntr(USF)=0,0
Exp/Cntr=0.3,0.1

Type RM Length L Ch R = 1 ,6905    ,79,81.4,84
XS GIS Cut Line= 2
2260274.85697435500430.5239389862260096.19540362500267.783096617
#Sta/Elev= 30
       0 2643.42     7.9 2639.97    14.4 2636.41    19.8 2633.85    30.7 2630.34
    37.6 2629.85    39.7 2629.43    42.5 2628.41    59.5 2617.33    63.1 2614.53
    67.3 2611.69      74  2607.9    85.2 2602.44    99.1 2598.31   106.4 2596.98
   113.3 2596.86   120.8 2597.12   133.5 2599.43   138.8 2601.26   152.9 2607.17
   156.4 2608.26   160.5 2608.48   167.1 2608.28   180.2 2608.79   186.9 2609.39
   192.6 2610.88     204  2616.7     218 2624.68   233.7 2631.43   241.7 2635.82
#Mann= 5 ,-1,0
       0     .05       0      40      .1       0   106.4    .045       0
   120.8      .1       0     190     .05       0
Bank Sta=106.4,120.8
XS Rating Curve= 0 ,0
Exp/Cntr(USF)=0,0
Exp/Cntr=0.3,0.1

Type RM Length L Ch R = 1 ,6824    ,94.5,86.4,81.2
XS GIS Cut Line= 4
2260324.13134912500391.4139908142260268.36173846500328.802857725
2260220.47847373500254.0029525882260158.37649176500221.295908747
#Sta/Elev= 30
       0 2644.55      12 2638.91    18.6  2635.2    24.2  2631.4    29.9 2629.39
    35.5 2626.37    40.5 2625.21    46.9 2624.68    49.7 2623.57    56.6 2617.77
      78 2601.88    89.5 2595.34    92.4 2594.29    97.6 2593.05   118.5 2592.04
   124.3 2591.71   127.72592.064   130.9 2593.39   136.1 2597.35   140.4 2599.15
   143.5 2599.53   172.7 2599.11     182 2599.45   195.6  2597.9   200.2 2598.36
   204.6 2599.85     212 2603.67   220.9 2609.06   226.8 2613.04   242.8 2622.43
#Mann= 5 ,-1,0
       0     .05       0      60      .1       0   118.5    .045       0
   127.7      .1       0  212.66     .05       0
Bank Sta=118.5,127.7
XS Rating Curve= 0 ,0
Exp/Cntr(USF)=0,0
Exp/Cntr=0.3,0.1

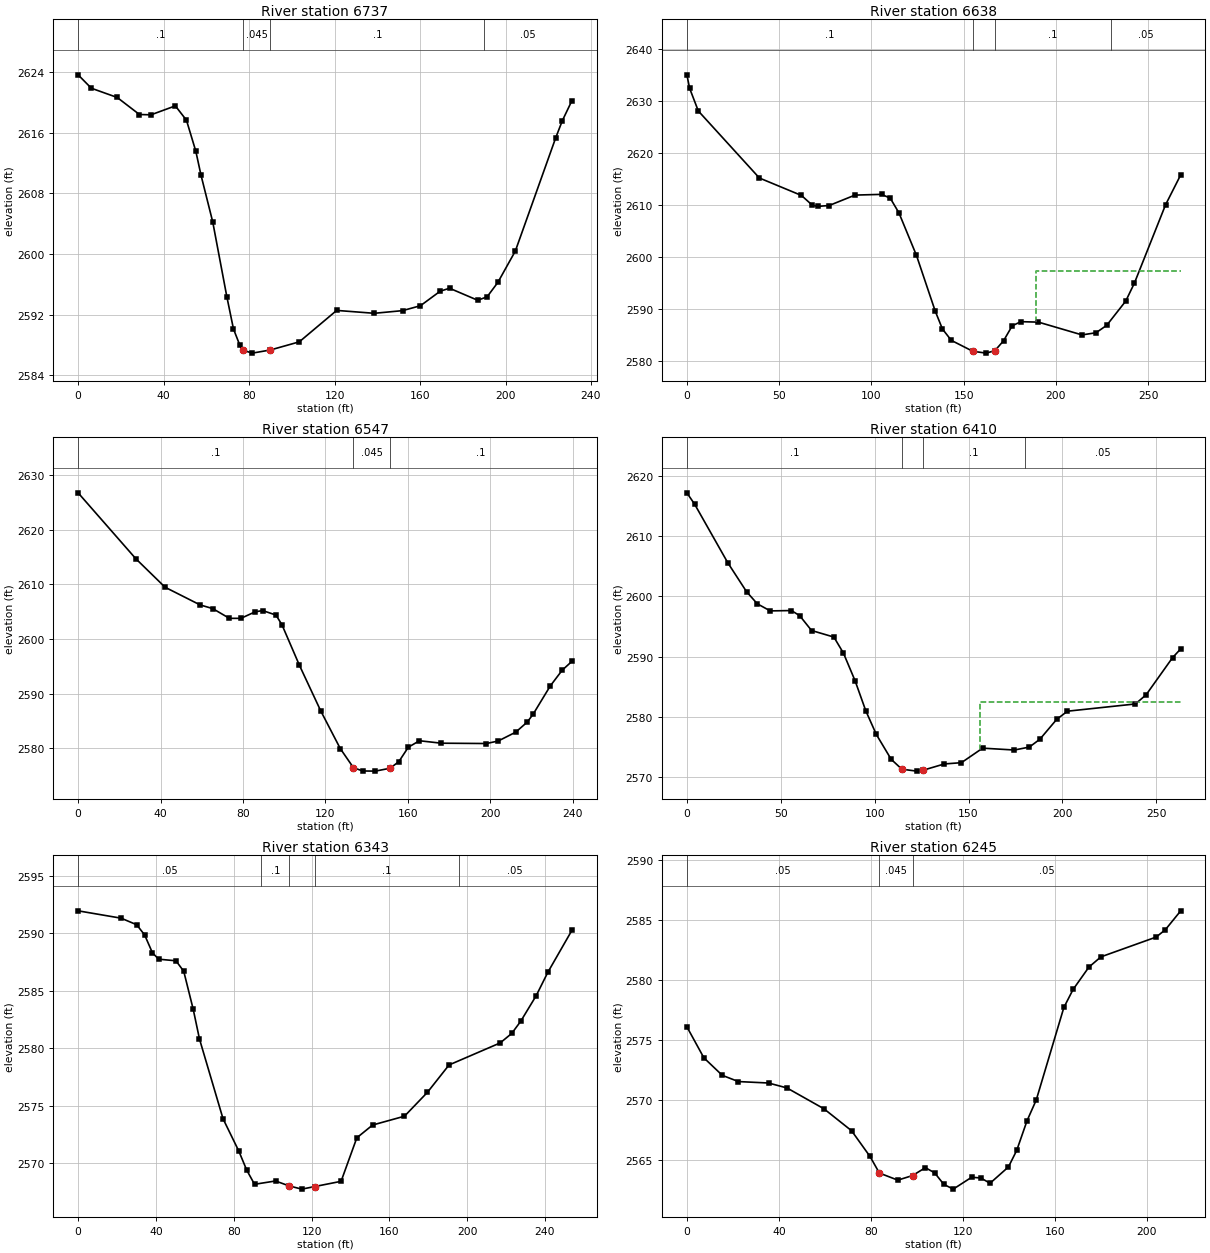
Type RM Length L Ch R = 1 ,6737    ,98.3,99.4,101
XS GIS Cut Line= 2
2260394.24697869500287.3717854142260184.12599433500191.231523703
#Sta/Elev= 30
       0 2623.67     6.2  2621.9    18.3 2620.68    28.7 2618.43    34.1 2618.39
    45.5 2619.57    50.7 2617.68    55.1 2613.56    57.5 2610.43      63 2604.24
    69.6 2594.37    72.7 2590.11    75.6 2588.02    77.1 2587.31    81.5 2586.92
      902587.337   103.5 2588.41     121 2592.56   138.6 2592.18   151.8 2592.53
   160.2 2593.18   169.4 2595.09   173.8 2595.49     187  2593.9   191.4 2594.36
   196.4 2596.25   204.6  2600.4   223.5 2615.36   226.6 2617.62   231.1 2620.27
#Mann= 4 ,-1,0
       0      .1       0    77.1    .045       0      90      .1       0
     190     .05       0
Bank Sta=77.1,90
XS Rating Curve= 0 ,0
Exp/Cntr(USF)=0,0
Exp/Cntr=0.3,0.1

Type RM Length L Ch R = 1 ,6638    ,88.3,91.2,94
XS GIS Cut Line= 2
2260473.44460784500241.5417662922260246.94335574500099.117187279
#Sta/Elev= 30
       0 2634.98     1.5 2632.39     6.2 2628.04    39.3 2615.17    62.1 2611.82
    67.9 2609.97    70.8 2609.72    77.1 2609.89    91.1 2611.89   105.5 2612.03
   110.2  2611.3   114.9 2608.49   124.4 2600.32   134.6 2589.59   138.5 2586.17
   143.3    2584   154.9 2581.91   162.2 2581.55   166.9 2582.02   171.6 2583.92
   176.3  2586.8     181 2587.59   190.5  2587.5   214.1 2585.05   221.7 2585.46
   227.5 2586.89   237.8 2591.54   242.5 2594.99   259.4 2610.04   267.6 2615.78
#Mann= 4 ,-1,0
       0      .1       0   154.9    .045       0   166.9      .1       0
     230     .05       0
#XS Ineff= 2 , 0
                          189.16         2597.34
Permanent Ineff=
       F       F
Bank Sta=154.9,166.9
XS Rating Curve= 0 ,0
Exp/Cntr(USF)=0,0
Exp/Cntr=0.3,0.1

Type RM Length L Ch R = 1 ,6547    ,136.2,136.7,135.8
XS GIS Cut Line= 2
2260503.18689301500209.6966845792260345.29881373500029.508029125
#Sta/Elev= 30
       0  2626.8      28 2614.72    42.2 2609.49    59.2 2606.25    65.3 2605.58
    73.4 2603.79      79 2603.79    85.8 2604.97    89.5 2605.22      96 2604.39
    98.9 2602.61   107.4 2595.16   117.7 2586.83   127.2 2579.91   133.6  2576.4
   138.1 2575.81   144.2 2575.78   151.42576.314   155.6 2577.52   160.2 2580.16
   165.6 2581.35   176.2  2580.9   198.1 2580.84   203.8  2581.3   212.3 2582.92
   217.9 2584.77   220.8 2586.24   229.1 2591.41   234.9  2594.3   239.6 2595.91
#Mann= 3 ,-1,0
       0      .1       0   133.6    .045       0   151.4      .1       0
Bank Sta=133.6,151.4
XS Rating Curve= 0 ,0
Exp/Cntr(USF)=0,0
Exp/Cntr=0.3,0.1

Type RM Length L Ch R = 1 ,6410    ,73.2,66.9,59
XS GIS Cut Line= 2
2260606.67703959500112.5838665632260420.85182089499926.541114425
#Sta/Elev= 30
       0 2617.19     4.2 2615.27    21.8 2605.59    31.8 2600.79    37.5 2598.79
    44.4 2597.61    55.7 2597.67    60.1 2596.81    66.4 2594.36    78.3 2593.27
    83.4  2590.6    89.6 2586.01    95.3 2581.03   100.9 2577.12   108.8    2573
   114.5 2571.36   122.4 2571.04   125.8 2571.19   137.1 2572.23   146.2 2572.44
   157.5 2574.85   174.4 2574.54   182.4 2575.03     188 2576.33     197 2579.64
   202.7 2580.98   238.9 2582.18   244.6 2583.71   258.7 2589.88     263 2591.31
#Mann= 4 ,-1,0
       0      .1       0   114.5    .045       0   125.8      .1       0
     180     .05       0
#XS Ineff= 2 , 0
                          156.01          2582.5
Permanent Ineff=
       F       F
Bank Sta=114.5,125.8
XS Rating Curve= 0 ,0
Exp/Cntr(USF)=0,0
Exp/Cntr=0.3,0.1

Type RM Length L Ch R = 1 ,6343    ,101.4,98.5,96
XS GIS Cut Line= 4
2260666.05703773499985.4768958312260612.19755807499978.744460874
2260502.07415771499962.3942616942260425.13204393499919.114322688
#Sta/Elev= 30
       0 2591.96    22.1 2591.32    30.1 2590.75    34.2 2589.86    38.2 2588.31
    41.4 2587.75    50.3 2587.61    54.3  2586.7    59.2 2583.37    62.4  2580.8
    74.5 2573.86    82.6 2571.05    86.7 2569.38    90.7 2568.15   101.5 2568.44
   108.5 2568.01     115 2567.73   121.62567.952   135.2 2568.41   143.3  2572.2
   151.4 2573.31   167.8 2574.08   179.6 2576.16   190.7 2578.54     217 2580.46
   222.9 2581.28   227.5 2582.33   235.5 2584.57   241.5 2586.61   253.9 2590.27
#Mann= 5 ,-1,0
       0     .05       0   94.28      .1       0   108.5    .045       0
   121.6      .1       0  195.61     .05       0
Bank Sta=108.5,121.6
XS Rating Curve= 0 ,0
Exp/Cntr(USF)=0,0
Exp/Cntr=0.3,0.1

Type RM Length L Ch R = 1 ,6245    ,125.4,133.4,137.2
XS GIS Cut Line= 2
2260651.57393137499866.3695902232260437.48840013 499883.21891444
#Sta/Elev= 30
       0 2576.12     7.4 2573.53    15.4 2572.07    22.4 2571.55    35.5 2571.43
    43.5 2571.02    59.6 2569.28    71.6 2567.45    79.6 2565.31    83.7 2563.92
    91.7 2563.33    98.12563.712   103.7 2564.37   107.7 2563.94   111.7 2562.98
   115.8 2562.58   123.8 2563.57   127.8 2563.51   131.8 2563.07   139.8 2564.43
   143.4 2565.81   147.9 2568.29   151.9 2570.02   163.9 2577.73   167.9 2579.23
   174.8  2581.1     180 2581.95     204  2583.6     208 2584.21   214.7 2585.79
#Mann= 3 ,-1,0
       0     .05       0    83.7    .045       0    98.1     .05       0
Bank Sta=83.7,98.1
XS Rating Curve= 0 ,0
Exp/Cntr(USF)=0,0
Exp/Cntr=0.3,0.1

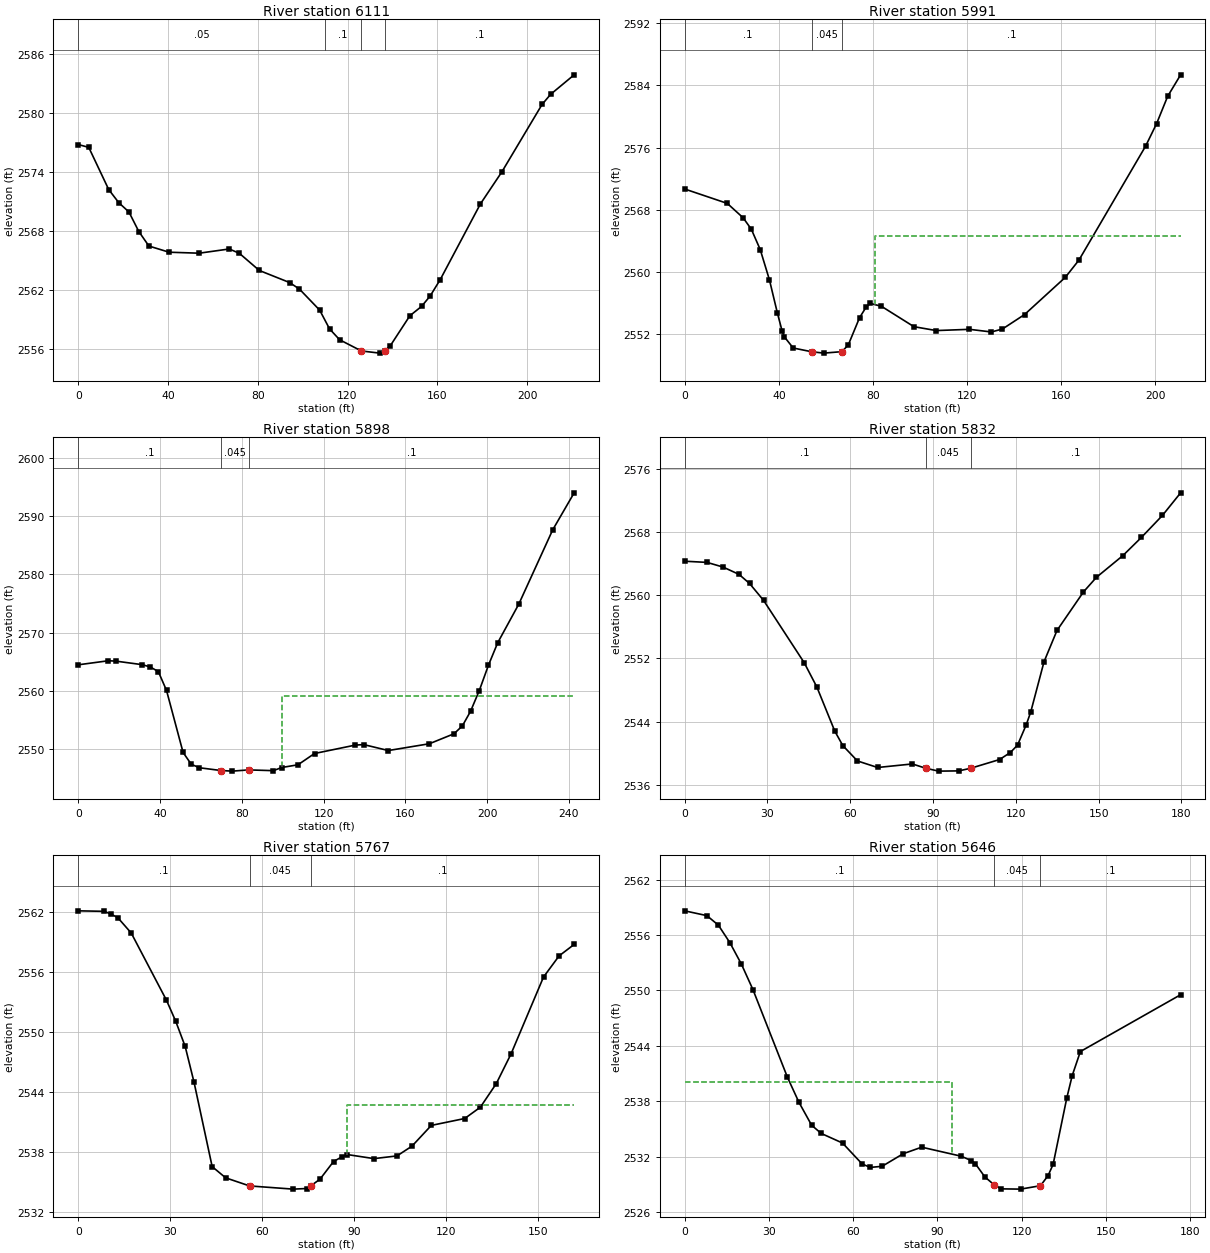
Type RM Length L Ch R = 1 ,6111    ,119.4,120.7,120.7
XS GIS Cut Line= 2
2260676.34781434499814.3798586492260478.78122842499715.376313084
#Sta/Elev= 30
       0  2576.8     4.7 2576.51    13.6 2572.21    18.1 2570.87    22.6 2569.93
      27 2567.94    31.5 2566.46    40.5 2565.83    53.9 2565.73    67.3 2566.16
    71.8 2565.72    80.7 2563.97    94.2 2562.74    98.6 2562.07   107.6 2559.93
     112 2558.02   116.5 2556.91   126.2 2555.77   134.4 2555.55   136.6 2555.81
   138.9 2556.24   147.8 2559.36     153 2560.31   156.8 2561.36   161.3 2563.03
   179.2 2570.74   188.8 2574.02   206.7 2580.88   210.5 2581.91     221  2583.9
#Mann= 4 ,-1,0
       0     .05       0     110      .1       0   126.2    .045       0
   136.6      .1       0
Bank Sta=126.2,136.6
XS Rating Curve= 0 ,0
Exp/Cntr(USF)=0,0
Exp/Cntr=0.3,0.1

Type RM Length L Ch R = 1 ,5991    ,96.7,92.1,86.1
XS GIS Cut Line= 2
2260683.61615027499691.831309701 2260503.4935706499582.597030673
#Sta/Elev= 30
       0 2570.69    18.1 2568.84    24.8    2567    28.3 2565.53    32.1  2562.9
      36 2559.02    39.4 2554.73    41.4 2552.43    42.3  2551.7    46.1 2550.25
    53.9 2549.77    59.1 2549.59    66.8 2549.78    69.5 2550.64    74.3 2554.15
    77.2 2555.56    78.9 2555.98    83.6 2555.61    97.4 2552.99   106.9 2552.49
     121 2552.65   130.3 2552.31     135 2552.69   144.4 2554.55   161.7 2559.33
   167.5 2561.55   195.8 2576.19   200.5  2579.1   205.2 2582.61   210.7 2585.37
#Mann= 3 ,-1,0
       0      .1       0    53.9    .045       0    66.8      .1       0
#XS Ineff= 2 , 0
                           80.92         2564.71
Permanent Ineff=
       F       F
Bank Sta=53.9,66.8
XS Rating Curve= 0 ,0
Exp/Cntr(USF)=0,0
Exp/Cntr=0.3,0.1

Type RM Length L Ch R = 1 ,5898    ,56.5,66.2,79.9
XS GIS Cut Line= 3
2260743.23853022499586.1981607512260550.56155211499568.357699815
2260506.85242282499546.057123645
#Sta/Elev= 30
       0 2564.47    14.8 2565.17    18.5  2565.1    31.2  2564.5    35.2 2564.11
    39.2  2563.3    43.2 2560.06    51.3  2549.4    55.3 2547.37    59.3 2546.77
    69.9 2546.29    75.4 2546.19    83.4  2546.4    95.5 2546.27    99.5 2546.81
   107.5 2547.28   115.6 2549.22   135.6 2550.67   139.7 2550.75   151.7 2549.73
   171.8  2550.9   183.8 2552.61   187.9 2553.96   191.9 2556.46   196.2 2560.05
   200.7 2564.42   205.2 2568.26   215.5 2574.89   232.1 2587.67   242.6 2594.04
#Mann= 3 ,-1,0
       0      .1       0    69.9    .045       0    83.4      .1       0
#XS Ineff= 2 , 0
                           99.84         2559.04
Permanent Ineff=
       F       F
Bank Sta=69.9,83.4
XS Rating Curve= 0 ,0
Exp/Cntr(USF)=0,0
Exp/Cntr=0.3,0.1

Type RM Length L Ch R = 1 ,5832    ,64.3,65.2,66.9
XS GIS Cut Line= 3
2260739.84808691499580.7816232912260700.99222327499555.490413867
2260628.44509111499443.565413913
#Sta/Elev= 30
       0 2564.33     8.1 2564.18    13.9 2563.59    19.7 2562.66    23.5 2561.51
    28.6 2559.36    43.3 2551.47    47.9 2548.38    54.4 2542.78    57.3 2540.96
    62.6 2539.01    69.9 2538.18    82.5 2538.63    87.3 2538.09      92 2537.72
    99.3 2537.75   103.6 2538.08   114.1 2539.19     118 2540.08   120.6 2541.01
   123.8 2543.63   125.4 2545.23   130.2 2551.58   134.9 2555.55   144.5 2560.44
   149.2 2562.29   158.8 2565.05   165.5 2567.35   173.1 2570.13   179.7    2573
#Mann= 3 ,-1,0
       0      .1       0    87.3    .045       0   103.6      .1       0
Bank Sta=87.3,103.6
XS Rating Curve= 0 ,0
Exp/Cntr(USF)=0,0
Exp/Cntr=0.3,0.1

Type RM Length L Ch R = 1 ,5767    ,123.6,120.9,117.2
XS GIS Cut Line= 3
 2260766.5445144499564.9372732852260723.23486426499470.384540338
2260686.92754369499425.379747347
#Sta/Elev= 30
       0 2562.07     8.5 2562.02    10.7 2561.74    12.9 2561.39    17.3 2559.85
    28.8 2553.13    31.8 2551.04    34.9 2548.51    37.8 2544.92    43.7  2536.5
    48.1 2535.38    55.9 2534.57    70.1 2534.25    74.5 2534.31    75.9 2534.58
    78.9 2535.25    83.3 2537.01    86.1 2537.49    87.7 2537.71    96.5  2537.3
     104 2537.57   108.9 2538.55   115.2 2540.62   126.1 2541.31   131.2 2542.44
   136.4  2544.8   141.2 2547.76   151.8 2555.45   156.9 2557.57   161.8 2558.71
#Mann= 3 ,-1,0
       0      .1       0    55.9    .045       0    75.9      .1       0
#XS Ineff= 2 , 0
                           87.54         2542.66
Permanent Ineff=
       F       F
Bank Sta=55.9,75.9
XS Rating Curve= 0 ,0
Exp/Cntr(USF)=0,0
Exp/Cntr=0.3,0.1

Type RM Length L Ch R = 1 ,5646    ,126.5,125.4,127.8
XS GIS Cut Line= 3
2260862.78153212499520.8606068672260851.31729377499471.553063462
2260779.86629971499367.827098682
#Sta/Elev= 30
       0 2558.62     7.9  2558.1      12 2557.07    16.1 2555.17    20.2 2552.85
    24.3  2550.1    36.6  2540.6    40.7 2537.89    45.2 2535.42    48.6 2534.53
    56.2 2533.49    63.2 2531.22    66.1 2530.85    70.3 2530.97    77.8 2532.33
    84.4 2533.04    98.5 2532.06   102.1 2531.58   103.5 2531.25   106.9 2529.82
   110.1 2528.99   112.6 2528.53   119.6  2528.5   126.7 2528.87   129.4 2529.96
   131.2 2531.18   136.1 2538.41     138 2540.79   140.9 2543.39   176.6 2549.54
#Mann= 3 ,-1,0
       0      .1       0   110.1    .045       0   126.7      .1       0
#XS Ineff= 2 , 0
           95.33 2540.14
Permanent Ineff=
       F       F
Bank Sta=110.1,126.7
XS Rating Curve= 0 ,0
Exp/Cntr(USF)=0,0
Exp/Cntr=0.3,0.1

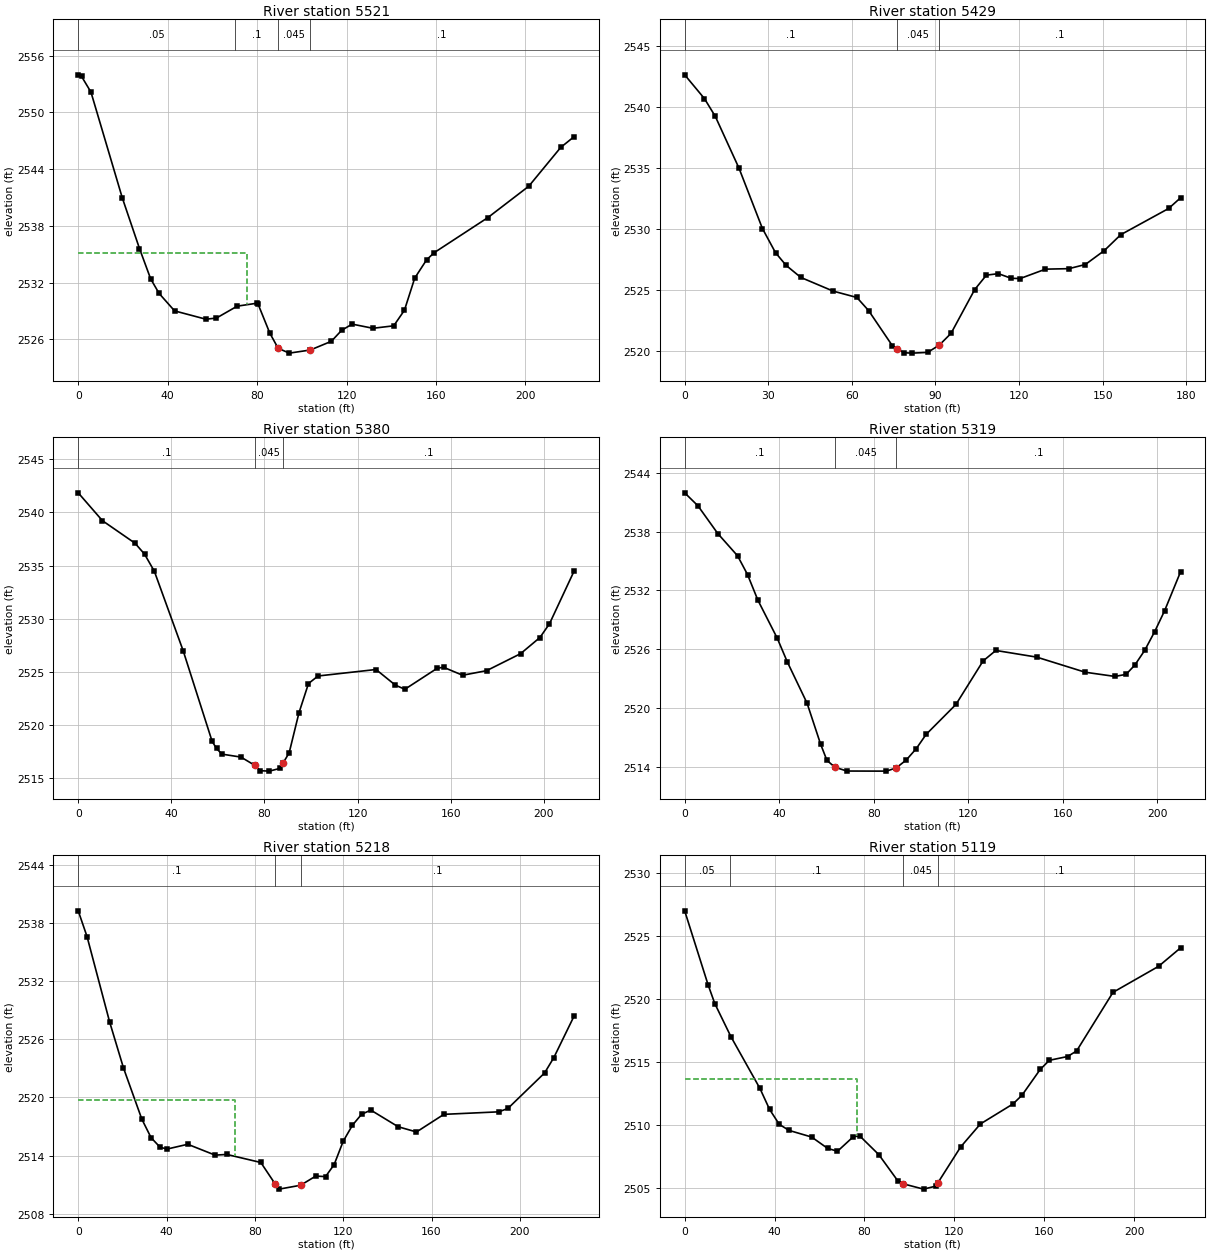
Type RM Length L Ch R = 1 ,5521    ,88.6,91.2,94.2
XS GIS Cut Line= 3
2260976.93309934499474.0791409542260897.90720032499343.061293058
2260834.60087672499316.027202834
#Sta/Elev= 30
       0 2553.98     1.5 2553.81     5.7 2552.15    19.7 2540.97    27.4  2535.6
    32.4 2532.39    36.2 2530.84    43.1    2529    57.1 2528.12    61.8 2528.24
    71.1  2529.5    79.9 2529.81    80.5 2529.68    85.7 2526.64   89.422525.041
    94.4 2524.53   103.8 2524.86   113.2 2525.78   117.8 2526.94   122.5  2527.6
   131.8 2527.16   141.1 2527.42   145.9 2529.07   150.5 2532.47   155.8  2534.4
   159.2 2535.16   183.2 2538.87   201.5 2542.19   215.8  2546.3   221.8 2547.44
#Mann= 4 ,-1,0
       0     .05       0      70      .1       0   89.42    .045       0
   103.8      .1       0
#XS Ineff= 2 , 0
           75.28 2535.14
Permanent Ineff=
       F       F
Bank Sta=89.42,103.8
XS Rating Curve= 0 ,0
Exp/Cntr(USF)=0,0
Exp/Cntr=0.3,0.1

Type RM Length L Ch R = 1 ,5429    ,49,49.8,50.9
XS GIS Cut Line= 3
2261026.78304225499419.5925427532260981.28986687499287.573131826
2260950.06906023499265.272555656
#Sta/Elev= 30
       0  2542.6     7.1 2540.65      11 2539.19    19.5 2534.95    27.9 2530.01
    32.6 2528.03    36.4 2526.99    41.7    2526    53.3 2524.88    61.8 2524.36
      66 2523.29    74.5 2520.42   76.262520.173    78.7 2519.83    81.7  2519.8
    87.2 2519.86    91.4 2520.46    95.6 2521.42   104.1 2525.01   108.3 2526.19
   112.6 2526.31   117.2 2525.93   120.4 2525.91   129.5 2526.68   137.9 2526.72
   143.8 2527.06   150.6  2528.2   156.5  2529.5   173.7 2531.65     178 2532.53
#Mann= 3 ,-1,0
       0      .1       0   76.26    .045       0    91.4      .1       0
Bank Sta=76.26,91.4
XS Rating Curve= 0 ,0
Exp/Cntr(USF)=0,0
Exp/Cntr=0.3,0.1

Type RM Length L Ch R = 1 ,5380    ,61.6,60.4,60
XS GIS Cut Line= 2
2261069.30810019499408.7563795222261014.48684411499202.936225138
#Sta/Elev= 30
       0 2541.84    10.4 2539.22    24.4  2537.1    28.5 2536.07    32.7 2534.46
    45.1 2526.97    57.5 2518.47    59.4 2517.79    61.7 2517.26    69.9 2516.98
    75.8 2516.21    78.2  2515.7    82.1 2515.66    86.5 2515.91    87.92516.391
    90.6 2517.38    94.8 2521.14    98.9  2523.9     103 2524.61   127.9 2525.22
   136.2 2523.75   140.3 2523.36   154.2 2525.34   156.9 2525.43   165.1 2524.68
   175.4 2525.11     190 2526.71   198.3 2528.23   202.4 2529.52     213 2534.49
#Mann= 3 ,-1,0
       0      .1       0    75.8    .045       0    87.9      .1       0
Bank Sta=75.8,87.9
XS Rating Curve= 0 ,0
Exp/Cntr(USF)=0,0
Exp/Cntr=0.3,0.1

Type RM Length L Ch R = 1 ,5319    ,100.4,100.8,101.1
XS GIS Cut Line= 2
2261129.77829382499386.5171196012261065.55263445499186.703957118
#Sta/Elev= 30
       0 2541.95     5.6 2540.63      14  2537.8    22.4 2535.52    26.6 2533.61
      31 2530.99    39.2 2527.11    43.4 2524.72    51.8 2520.49    57.5 2516.33
    60.2 2514.66   63.522513.967    68.6 2513.57    85.4 2513.56    89.6  2513.9
    93.8  2514.7      98 2515.85   102.2 2517.31   114.8 2520.36   126.3  2524.8
   131.7 2525.87     149 2525.19   169.5 2523.65   182.1 2523.22   186.8 2523.43
   190.5 2524.37   194.7 2525.88   198.9 2527.78   203.1 2529.91   209.9 2533.91
#Mann= 3 ,-1,0
       0      .1       0   63.52    .045       0    89.6      .1       0
Bank Sta=63.52,89.6
XS Rating Curve= 0 ,0
Exp/Cntr(USF)=0,0
Exp/Cntr=0.3,0.1

Type RM Length L Ch R = 1 ,5218    ,105.6,99.7,92
XS GIS Cut Line= 2
2261225.82299854499373.0046525662261166.94947745499156.243052194
#Sta/Elev= 30
       0 2539.26       4  2536.6    14.2 2527.81    20.5 2523.04    28.8 2517.76
      33 2515.84    37.1 2514.85    40.3 2514.67    49.6 2515.16      62 2514.04
    67.3 2514.11    82.7 2513.28    89.2 2511.06      91 2510.53   100.72510.929
   107.6 2511.88     112 2511.82   115.9 2513.06     120 2515.47   124.2 2517.13
   128.3 2518.25   132.5 2518.69   144.9 2516.97   153.2 2516.43   165.6 2518.25
   190.5 2518.51   194.6 2518.86   211.2 2522.52   215.4 2524.11   224.6 2528.41
#Mann= 3 ,-1,0
       0      .1       0    89.2    .045       0   100.7      .1       0
#XS Ineff= 2 , 0
           70.85 2519.68
Permanent Ineff=
       F       F
Bank Sta=89.2,100.7
XS Rating Curve= 0 ,0
Exp/Cntr(USF)=0,0
Exp/Cntr=0.3,0.1

Type RM Length L Ch R = 1 ,5119    ,45.8,48.6,53.1
XS GIS Cut Line= 4
2261338.54372272 499336.279516872261310.50794001 499266.11792686
2261260.39938841499218.702349237 2261248.3290943 499143.53952183
#Sta/Elev= 30
       0 2527.01    10.4 2521.14    13.4 2519.64    20.6    2517    33.5 2512.89
    37.8 2511.22    42.1 2510.04    46.4 2509.56    56.5 2509.03    63.6 2508.13
      68  2507.9      75 2509.05    77.9 2509.12    86.4 2507.63    94.8 2505.56
   97.212505.313   106.3 2504.89   111.8 2505.13  112.752505.412   122.8 2508.24
   131.6 2510.07   146.1 2511.66   150.1 2512.35   158.2  2514.4   162.3 2515.13
   170.4 2515.43   174.4 2515.87   190.6 2520.53   210.9  2522.6   220.7 2524.07
#Mann= 4 ,-1,0
       0     .05       0      20      .1       0   97.21    .045       0
  112.75      .1       0
#XS Ineff= 2 , 0
           76.49 2513.67
Permanent Ineff=
       F       F
Bank Sta=97.21,112.75
XS Rating Curve= 0 ,0
Exp/Cntr(USF)=0,0
Exp/Cntr=0.3,0.1

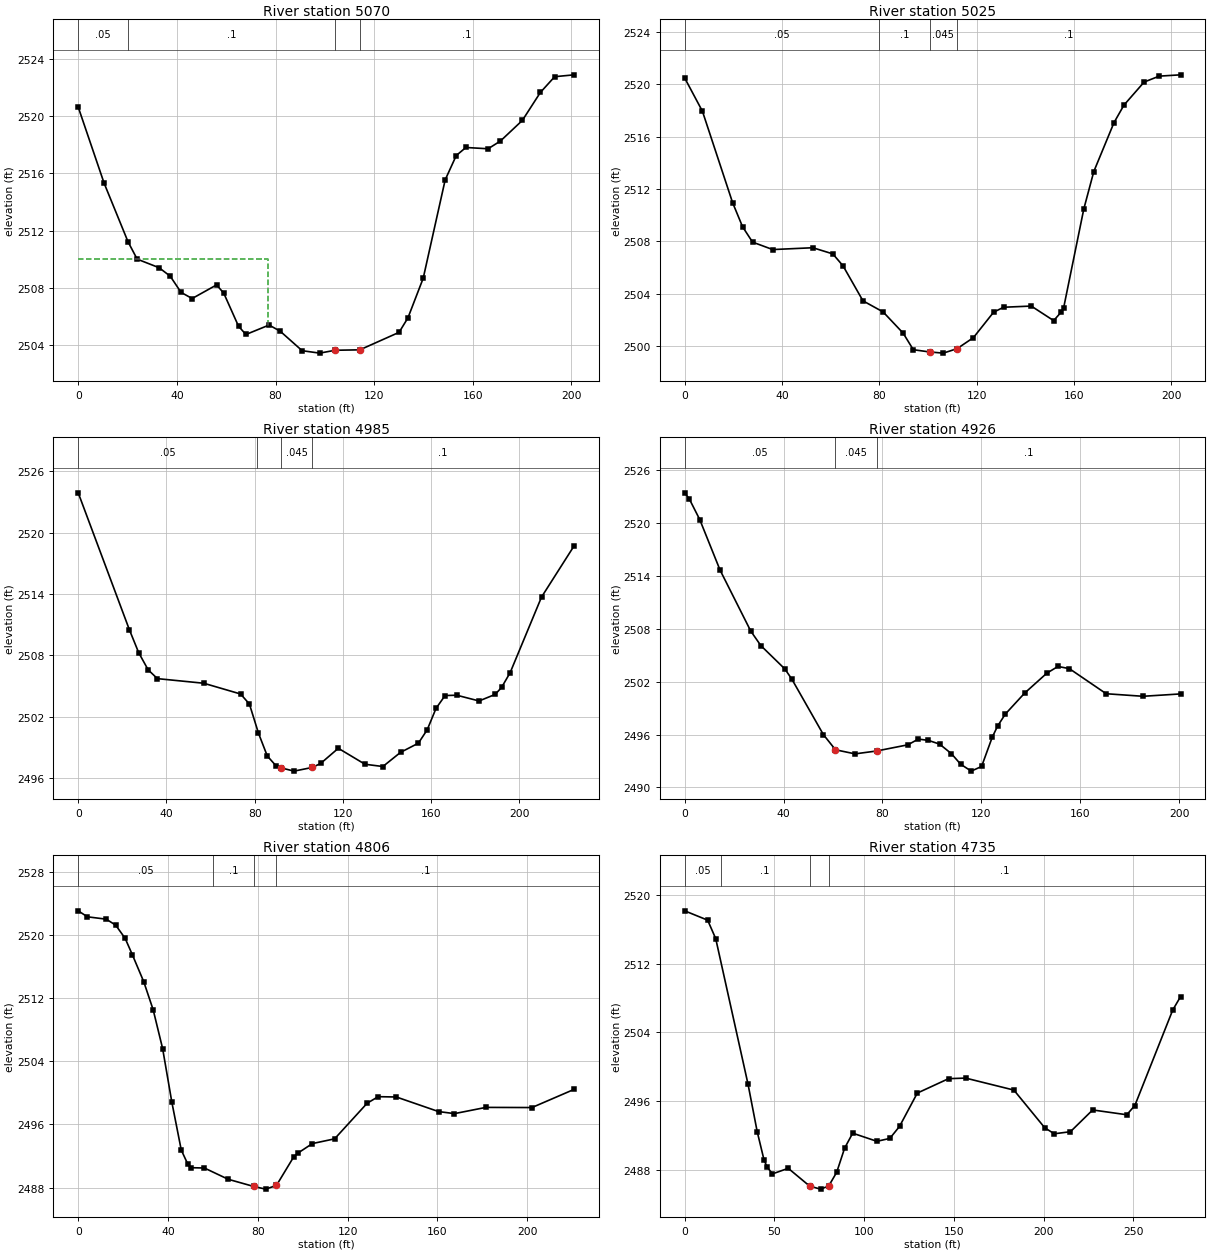
Type RM Length L Ch R = 1 ,5070    ,43.3,45.7,47.6
XS GIS Cut Line= 2
 2261373.8988243 499310.563039292261284.69651962499130.374383837
#Sta/Elev= 30
       0 2520.63    10.5 2515.32    20.2 2511.23    23.9 2510.02    32.8 2509.42
    37.3 2508.83    41.7  2507.7    46.2 2507.27    56.1 2508.22      59 2507.65
      65 2505.34      68 2504.76    77.4 2505.42    81.9 2504.99    90.8 2503.63
    97.9 2503.46   104.2 2503.66   114.2 2503.69   130.1 2504.91   133.7 2505.92
   139.9 2508.69   148.8 2515.55   153.3 2517.25   157.2 2517.81   166.2 2517.72
   171.2 2518.26   180.1  2519.7   187.4 2521.65   193.2 2522.75   201.1 2522.88
#Mann= 4 ,-1,0
       0     .05       0      20      .1       0   104.2    .045       0
   114.2      .1       0
#XS Ineff= 2 , 0
           76.89 2510.02
Permanent Ineff=
       F       F
Bank Sta=104.2,114.2
XS Rating Curve= 0 ,0
Exp/Cntr(USF)=0,0
Exp/Cntr=0.3,0.1

Type RM Length L Ch R = 1 ,5025    ,34.2,39.1,42.1
XS GIS Cut Line= 2
2261394.13959979499300.2602004092261344.12722582499102.615145615
#Sta/Elev= 30
       0 2520.47     7.3 2517.93    19.7 2510.96    23.8 2509.12    27.9 2507.95
    36.2 2507.38    52.7 2507.52    60.9 2507.05    65.1 2506.14    73.3 2503.47
    81.6 2502.62    89.8 2501.01      94 2499.74   100.7 2499.57   106.3 2499.48
     112 2499.82   118.7 2500.66     127  2502.6   131.1 2502.98   142.5 2503.07
   151.7 2501.96   154.8 2502.61   155.8 2502.93   164.1 2510.48   168.2 2513.33
   176.5 2517.06   180.6  2518.4   188.9 2520.16   195.1 2520.61   203.9 2520.71
#Mann= 4 ,-1,0
       0     .05       0      80      .1       0   100.7    .045       0
     112      .1       0
Bank Sta=100.7,112
XS Rating Curve= 0 ,0
Exp/Cntr(USF)=0,0
Exp/Cntr=0.3,0.1

Type RM Length L Ch R = 1 ,4985    ,54.1,59.2,59.6
XS GIS Cut Line= 4
2261424.28666376499295.2927811052261402.34252597499227.552842481
2261414.16963159499129.5976680122261367.67676848 499100.43797525
#Sta/Elev= 30
       0 2523.88    23.2 2510.51    27.4 2508.28    31.7  2506.6    35.9 2505.74
    56.9 2505.29    73.6 2504.24    77.6 2503.26    81.7 2500.42    85.7 2498.19
    89.7 2497.22   92.082497.023    97.8 2496.71106.10622497.069   109.9 2497.46
   117.9 2498.94     130 2497.38   138.1 2497.16   146.1 2498.54   154.2 2499.44
   158.2 2500.75   162.2 2502.84   166.3 2504.09   171.6 2504.12   181.7 2503.56
     189  2504.2   191.9 2504.88   195.8 2506.33     210  2513.7   224.8 2518.71
#Mann= 4 ,-1,0
       0     .05       0   81.21      .1       0   92.08    .045       0
106.1062      .1       0
Bank Sta=92.08,106.1062
XS Rating Curve= 0 ,0
Exp/Cntr(USF)=0,0
Exp/Cntr=0.3,0.1

Type RM Length L Ch R = 1 ,4926    ,126.1,120.6,109.1
XS GIS Cut Line= 4
2261457.06690713499287.0442007172261447.56020042499249.523584585
 2261479.5307176499163.2170569752261448.04817761499100.879480466
#Sta/Elev= 30
       0 2523.45     1.9 2522.74     6.1 2520.41    14.3 2514.68    26.7 2507.76
    30.8  2506.1    40.5 2503.45    43.3 2502.31    56.1 2495.9960.997432494.265
    68.9  2493.8  77.5972494.126    90.3 2494.83    94.5 2495.48    98.6 2495.33
   103.1 2494.91   107.9 2493.82   111.6 2492.63   115.9 2491.84   120.1 2492.37
   124.4 2495.69   126.6 2496.97   129.7 2498.32   137.5  2500.7   146.5 2502.97
     151 2503.73   155.6 2503.48   170.5 2500.63   185.4 2500.34   200.6 2500.61
#Mann= 3 ,-1,0
       0     .05       060.99743    .045       0  77.597      .1       0
Bank Sta=60.99743,77.597
XS Rating Curve= 0 ,0
Exp/Cntr(USF)=0,0
Exp/Cntr=0.3,0.1

Type RM Length L Ch R = 1 ,4806    ,72.3,70.6,68.6
XS GIS Cut Line= 3
2261590.22221163 499277.141977852261560.25274518 499177.51077024
2261493.90028431499081.371615354
#Sta/Elev= 30
       0 2523.11     4.1 2522.35    12.5 2522.05    16.7 2521.29    20.9 2519.62
    24.1 2517.55    29.2 2514.11    33.4 2510.54    37.6 2505.63    41.7 2498.84
    45.9 2492.76    48.8 2490.98    50.1 2490.52    56.2 2490.48    66.8 2489.05
 78.21512488.135    83.5  2487.8    88.3 2488.27      96  2491.9    97.9 2492.38
   104.3 2493.58   114.2 2494.18   128.7  2498.7   133.6 2499.53   141.7 2499.49
   160.5 2497.64   167.6 2497.38   181.6 2498.17   202.1 2498.15   220.9 2500.46
#Mann= 4 ,-1,0
       0     .05       0      60      .1       0 78.2151    .045       0
    88.3      .1       0
Bank Sta=78.2151,88.3
XS Rating Curve= 0 ,0
Exp/Cntr(USF)=0,0
Exp/Cntr=0.3,0.1

Type RM Length L Ch R = 1 ,4735    ,64.8,65.2,65.7
XS GIS Cut Line= 2
2261666.51624261 499240.601480472261541.03044386498994.439638728
#Sta/Elev= 30
       0  2518.2    12.8 2517.11    17.3 2514.95    35.3 2497.96    40.4 2492.43
    44.2 2489.13    45.9 2488.31    48.9  2487.5    57.7 2488.15    69.7 2486.06
    75.7 2485.72    80.2 2486.07    84.7 2487.69    89.1  2490.5    93.6 2492.25
   107.1  2491.3   114.3 2491.64   119.7 2493.04   129.6 2496.93     147 2498.61
   156.5 2498.68   183.4 2497.28   200.6 2492.88   205.9 2492.18   214.9 2492.42
   227.3 2494.96   246.3  2494.4   250.8 2495.48   271.9 2506.62   276.3  2508.2
#Mann= 4 ,-1,0
       0     .05       0      20      .1       0    69.7    .045       0
    80.2      .1       0
Bank Sta=69.7,80.2
XS Rating Curve= 0 ,0
Exp/Cntr(USF)=0,0
Exp/Cntr=0.3,0.1