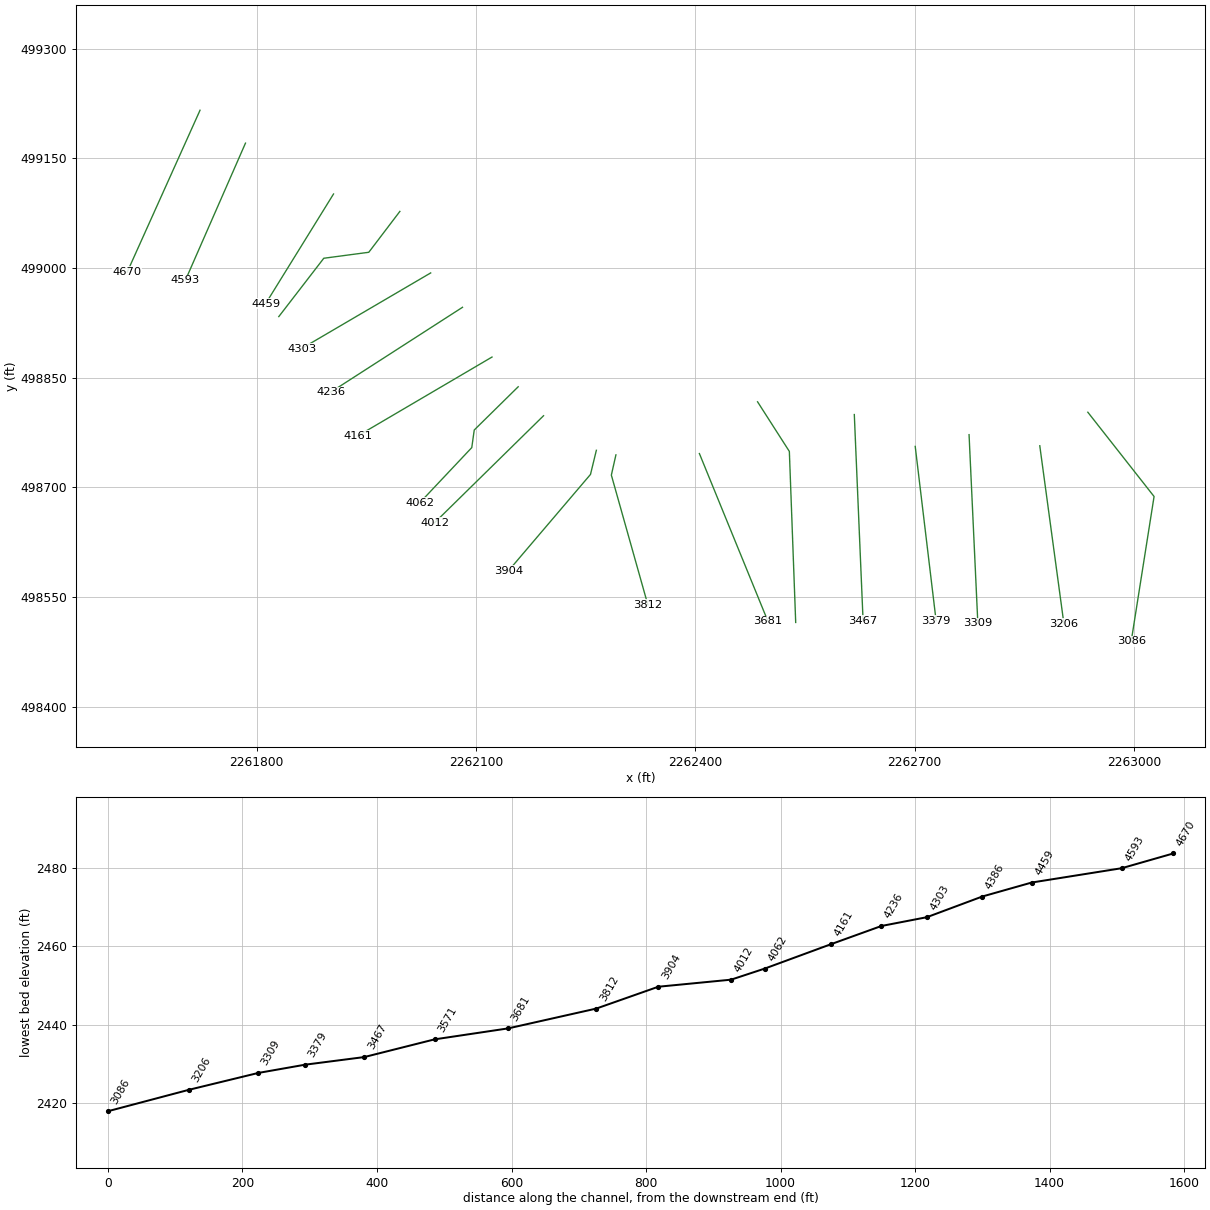
HEC-RAS study ELKLCKRN1.prj: ELKLCKRN1

--- ELKLCKRN1.g01 (geometry) --- (continued)

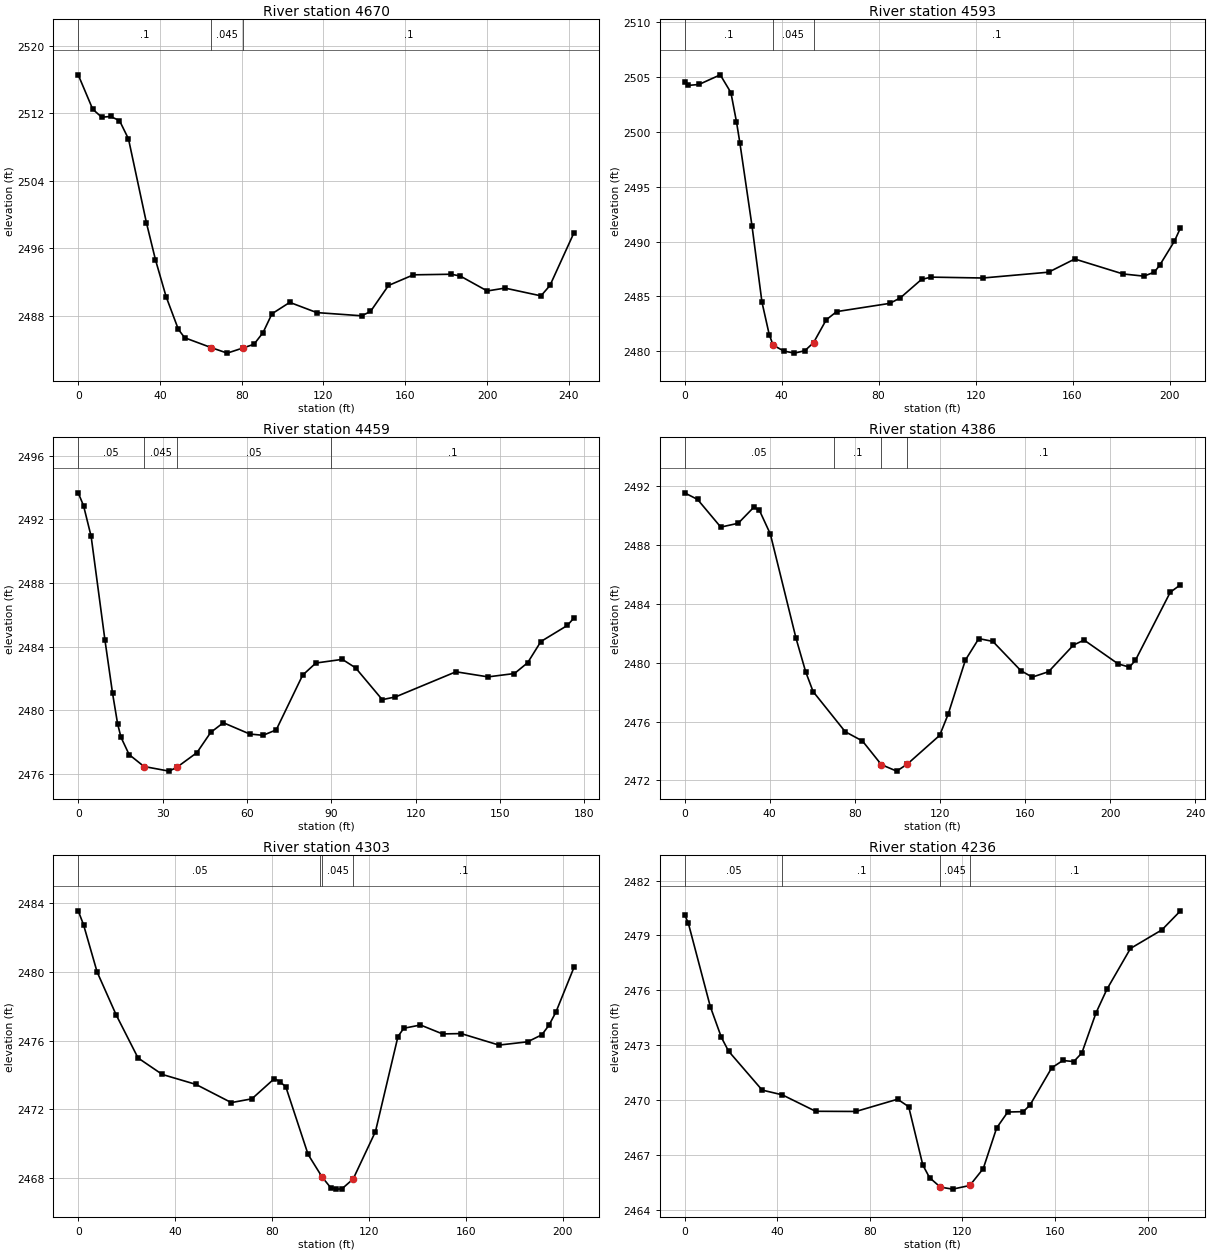
Type RM Length L Ch R = 1 ,4670    ,76.7,76.9,76.8
XS GIS Cut Line= 2
2261722.58624802499215.6238752422261623.04238831  498994.4152981
#Sta/Elev= 30
       0 2516.56     7.1 2512.49    11.5 2511.54    15.8 2511.63    20.2 2511.14
    24.6 2508.97    33.4 2499.02    37.8 2494.66      43  2490.3      49 2486.42
    52.1 2485.43      652484.269    72.9 2483.61    80.72484.228      86 2484.66
    90.4 2486.03    94.8 2488.27   103.5 2489.62   116.7 2488.41   138.7 2488.03
     143 2488.54   151.8 2491.62     164 2492.88   182.5 2492.95   186.9 2492.74
   200.1 2490.97   208.8 2491.31   226.4 2490.39   230.8 2491.62   242.6 2497.89
#Mann= 3 ,-1,0
       0      .1       0      65    .045       0    80.7      .1       0
Bank Sta=65,80.7
XS Rating Curve= 0 ,0
Exp/Cntr(USF)=0,0
Exp/Cntr=0.3,0.1

Type RM Length L Ch R = 1 ,4593    ,135.7,133.8,132.7
XS GIS Cut Line= 2
2261784.74260331499170.628900067  2261702.676483498983.304060239
#Sta/Elev= 30
       0 2504.52     1.6 2504.22     5.9  2504.3    14.7 2505.18    19.1 2503.56
    21.4  2500.9    22.8 2498.98    27.8 2491.42    31.9 2484.49    34.9 2481.53
    36.5 2480.57    40.9 2480.03    45.3 2479.84    49.6 2480.06    53.2  2480.8
    58.4 2482.87    62.7 2483.62    84.6 2484.37    88.9 2484.86    97.7 2486.55
   101.7 2486.76     123 2486.68   150.1 2487.21   160.9 2488.41   180.8 2487.05
   189.4 2486.85   193.7 2487.21   195.9 2487.83     202 2490.03   204.5 2491.24
#Mann= 3 ,-1,0
       0      .1       0    36.5    .045       0    53.2      .1       0
Bank Sta=36.5,53.2
XS Rating Curve= 0 ,0
Exp/Cntr(USF)=0,0
Exp/Cntr=0.3,0.1

Type RM Length L Ch R = 1 ,4459    ,84,73.4,64.8
XS GIS Cut Line= 2
2261905.16571463499101.0511024162261812.39531776498951.191230554
#Sta/Elev= 30
       0 2493.67     1.9 2492.86     4.6 2490.93     9.5 2484.43    12.2 2481.09
      14 2479.17    15.2 2478.32    18.1 2477.23    23.4 2476.48    32.3 2476.19
    35.12476.433    42.2 2477.35    47.1 2478.62    51.6 2479.23      61 2478.52
    65.7 2478.44    70.4 2478.78    79.8 2482.22    84.5 2482.98    93.9 2483.21
    98.6 2482.68   108.1 2480.68   112.8 2480.85   134.3 2482.43   145.7 2482.11
   155.1 2482.32   159.8    2483   164.5 2484.33   173.9 2485.34   176.3 2485.82
#Mann= 4 ,-1,0
       0     .05       0    23.4    .045       0    35.1     .05       0
      90      .1       0
Bank Sta=23.4,35.1
XS Rating Curve= 0 ,0
Exp/Cntr(USF)=0,0
Exp/Cntr=0.3,0.1

Type RM Length L Ch R = 1 ,4386    ,78.5,82.4,87.4
XS GIS Cut Line= 4
 2261995.8915129499077.2407906192261953.41258939499021.345037926
2261891.85889836499013.1699383362261830.30520733 498933.34249528
#Sta/Elev= 30
       0 2491.55     6.1  2491.1      17 2489.22    25.2 2489.48    32.6 2490.58
    35.2 2490.35    40.3 2488.75    52.4 2481.65    56.9 2479.39    60.4 2478.04
    75.5 2475.31    83.6 2474.68    92.5 2473.07    99.7 2472.63   104.72473.108
   119.9 2475.06   123.9  2476.5     132 2480.18   138.3 2481.64   144.9 2481.45
     158 2479.47   163.4 2479.02   171.1 2479.39   182.8  2481.2   187.8 2481.54
   203.8 2479.92   209.1  2479.7   211.9 2480.16   228.3 2484.79   233.1  2485.3
#Mann= 4 ,-1,0
       0     .05       0      70      .1       0    92.5    .045       0
   104.7      .1       0
Bank Sta=92.5,104.7
XS Rating Curve= 0 ,0
Exp/Cntr(USF)=0,0
Exp/Cntr=0.3,0.1

Type RM Length L Ch R = 1 ,4303    ,67.2,67.6,68.2
XS GIS Cut Line= 2
 2262038.0771486498993.1163137542261861.45658533498889.641640325
#Sta/Elev= 30
       0 2483.57     2.2 2482.76     7.8 2480.01    15.7  2477.5    24.7    2475
    34.7 2474.04    48.6 2473.46    63.2  2472.4    71.7 2472.62      81  2473.8
    83.2 2473.62    85.7 2473.32    94.9 2469.38   100.7 2468.06   104.2 2467.45
   106.6 2467.36   108.8 2467.37   113.5 2467.95   122.7 2470.71     132 2476.25
   134.4 2476.73   141.3 2476.92   150.4  2476.4   158.1 2476.42   173.7 2475.75
   185.5 2475.94   191.4 2476.35   194.3  2476.9   197.2 2477.67   204.7 2480.29
#Mann= 4 ,-1,0
       0     .05       0     100      .1       0   100.7    .045       0
   113.5      .1       0
Bank Sta=100.7,113.5
XS Rating Curve= 0 ,0
Exp/Cntr(USF)=0,0
Exp/Cntr=0.3,0.1

Type RM Length L Ch R = 1 ,4236    ,75,74.5,74
XS GIS Cut Line= 2
2262081.54317165498946.0721080292261901.47725258498830.124617112
#Sta/Elev= 30
       0 2480.14     1.6 2479.68    11.1 2475.11    15.9 2473.42      19 2472.67
    33.5 2470.54    42.2 2470.28    56.6 2469.38      74 2469.37      92 2470.04
    96.8 2469.63   102.9 2466.44   105.8 2465.75   110.52465.228   115.8 2465.12
   123.2 2465.32     129 2466.24   134.8 2468.47   139.6 2469.34   146.3 2469.36
   149.2 2469.72   158.6 2471.76   163.4 2472.16   168.1  2472.1   171.6 2472.57
   177.7 2474.76   182.4 2476.05   192.6 2478.29   206.2 2479.31   214.2 2480.35
#Mann= 4 ,-1,0
       0     .05       0    42.2      .1       0   110.5    .045       0
   123.2      .1       0
Bank Sta=110.5,123.2
XS Rating Curve= 0 ,0
Exp/Cntr(USF)=0,0
Exp/Cntr=0.3,0.1

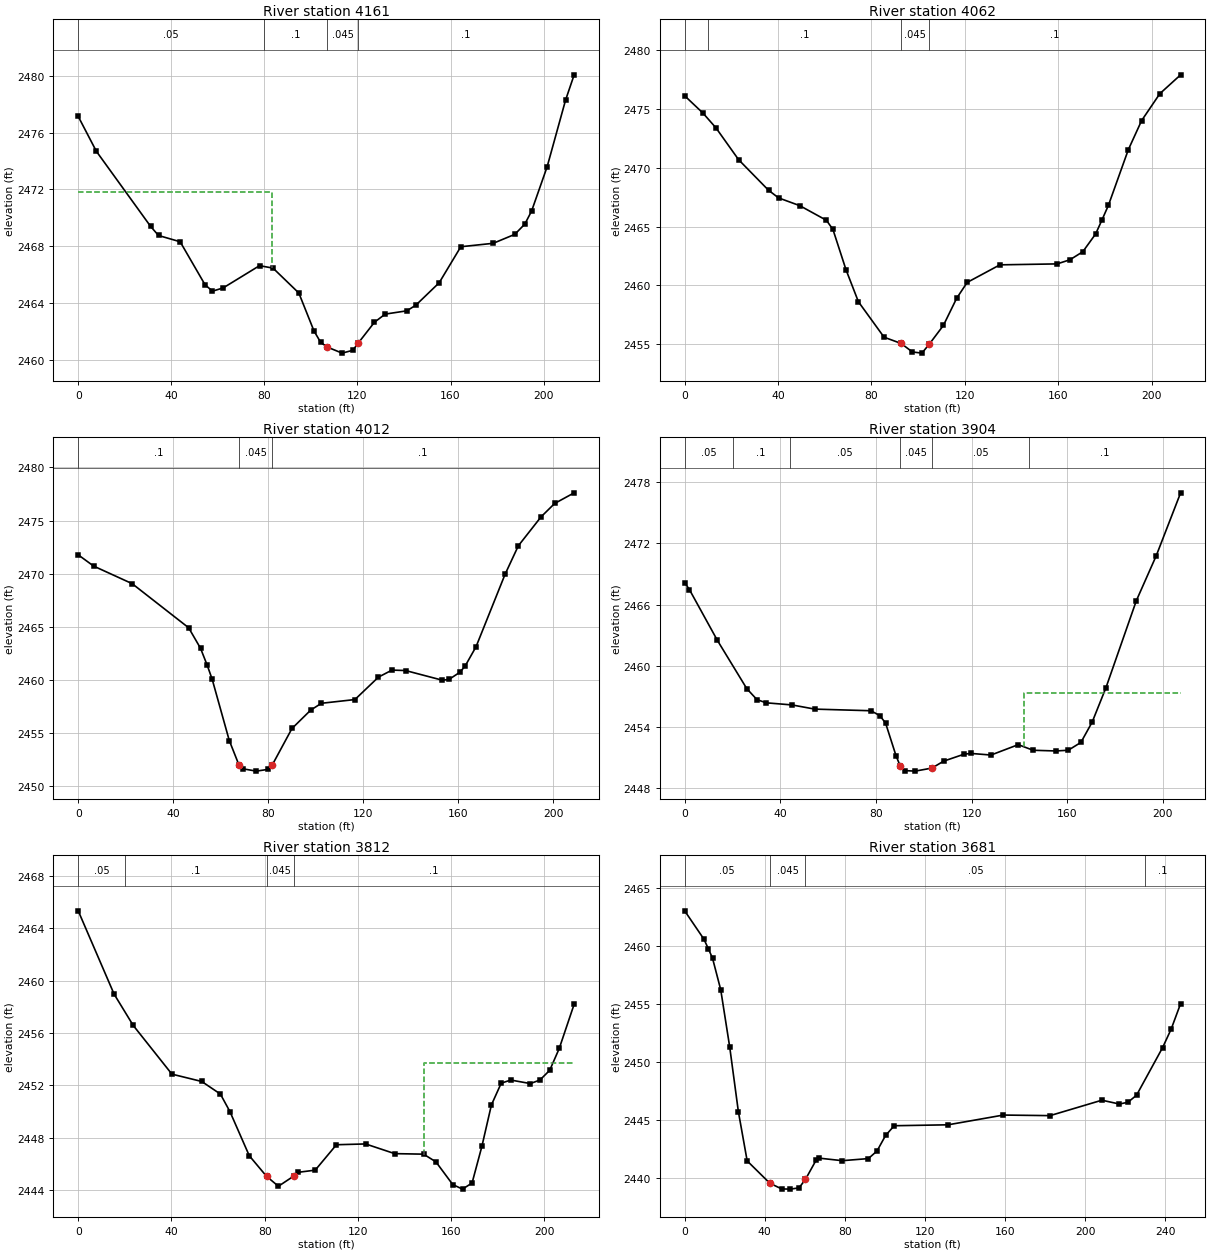
Type RM Length L Ch R = 1 ,4161    ,88,99.1,107.1
XS GIS Cut Line= 2
  2262121.927315498878.0453407162261938.17056736498770.110552054
#Sta/Elev= 30
       0 2477.13     7.8 2474.68    31.1 2469.41    34.5 2468.77    43.8 2468.33
    54.5 2465.31    57.7 2464.86    62.3 2465.09    77.9 2466.65    83.7 2466.48
    94.8 2464.73   101.3 2462.07   104.2 2461.26   107.1 2460.93   113.4 2460.51
     118 2460.71   120.2 2461.19   127.3 2462.68   131.9 2463.25   141.2 2463.48
   145.1 2463.88   155.1 2465.45   164.4 2467.98   178.3 2468.22   187.6 2468.85
   191.9 2469.57   194.8 2470.48   201.5  2473.6   209.4 2478.27   213.1 2480.05
#Mann= 4 ,-1,0
       0     .05       0      80      .1       0   107.1    .045       0
   120.2      .1       0
#XS Ineff= 2 , 0
           83.33 2471.79
Permanent Ineff=
       F       F
Bank Sta=107.1,120.2
XS Rating Curve= 0 ,0
Exp/Cntr(USF)=0,0
Exp/Cntr=0.3,0.1

Type RM Length L Ch R = 1 ,4062    ,57.3,49.9,43.3
XS GIS Cut Line= 4
2262157.73723711498837.3913723032262097.62621071498778.242122328
2262094.25999324498754.1977117692262023.08853798498678.698262614
#Sta/Elev= 30
       0 2476.09     7.8 2474.63    13.4 2473.37    23.1 2470.67    35.9 2468.08
    40.2 2467.43    49.3 2466.77    60.7 2465.53    63.5 2464.75    69.1 2461.33
    74.4 2458.62    85.4 2455.61    92.72455.081    97.5 2454.36   101.6 2454.26
   104.82455.032   110.8 2456.61   116.5 2458.92     121 2460.26     135 2461.75
   159.5 2461.83     165 2462.18   170.5 2462.86     176 2464.37   178.7 2465.55
   181.5 2466.81     190 2471.52   195.7 2473.99   203.5 2476.27   212.4 2477.87
#Mann= 4 ,-1,0
       0     .05       0      10      .1       0    92.7    .045       0
   104.8      .1       0
Bank Sta=92.7,104.8
XS Rating Curve= 0 ,0
Exp/Cntr(USF)=0,0
Exp/Cntr=0.3,0.1

Type RM Length L Ch R = 1 ,4012    ,107,108.2,109.2
XS GIS Cut Line= 2
 2262192.3971357498797.7632665042262043.42928688498651.471486829
#Sta/Elev= 30
       0 2471.78     6.5 2470.72    22.7 2469.07    46.5 2464.92    51.5 2462.99
    54.3  2461.4    56.4 2460.08    63.6 2454.32    67.6 2452.06    69.3 2451.66
      75 2451.44    79.8  2451.6   81.63 2451.99      90 2455.45    97.9 2457.18
   102.4 2457.82   116.5 2458.17   126.4 2460.28   132.1 2460.94   137.8  2460.9
   153.3 2459.99   156.1 2460.06   160.7 2460.74   162.9 2461.32   167.5 2463.14
   179.7 2469.94   185.3 2472.63   194.9 2475.36   200.6 2476.61   208.8 2477.61
#Mann= 3 ,-1,0
       0      .1       0    67.6    .045       0   81.63      .1       0
Bank Sta=67.6,81.63
XS Rating Curve= 0 ,0
Exp/Cntr(USF)=0,0
Exp/Cntr=0.3,0.1

Type RM Length L Ch R = 1 ,3904    ,81.3,92.1,103.5
XS GIS Cut Line= 3
2262264.65100249498750.4860450242262256.62279506498717.481192292
2262144.22789117498585.461781366
#Sta/Elev= 30
       0 2468.15       2 2467.46    13.7 2462.47      26 2457.73    30.2 2456.67
      34 2456.35    44.9 2456.14    54.4 2455.73    77.9 2455.57    81.6 2455.09
      84 2454.37    88.4 2451.14    90.2 2450.11    92.1 2449.69    96.4 2449.64
   103.4 2449.94   108.3 2450.62   116.8  2451.3   119.6 2451.38   128.1 2451.22
   139.5 2452.24   145.7 2451.69   155.2 2451.62   160.4 2451.69   165.7 2452.46
   170.4 2454.45   176.2 2457.85   188.9 2466.39   197.2 2470.79   207.4 2476.97
#Mann= 6 ,-1,0
       0     .05       0      20      .1       0   43.97     .05       0
    90.2    .045       0   103.4     .05       0  143.97      .1       0
#XS Ineff= 2 , 0
                          141.71         2457.35
Permanent Ineff=
       F       F
Bank Sta=90.2,103.4
XS Rating Curve= 0 ,0
Exp/Cntr(USF)=0,0
Exp/Cntr=0.3,0.1

Type RM Length L Ch R = 1 ,3812    ,129.5,131,132.6
XS GIS Cut Line= 3
2262291.41169389498744.2418836962262285.16753256498716.589169246
2262335.12082318498539.076582933
#Sta/Elev= 30
       0 2465.33    15.4 2458.97    23.6 2456.58    40.2 2452.86      53  2452.3
      61 2451.34    65.1    2450    73.4 2446.63    80.8 2445.06    85.9  2444.3
   92.582445.087    94.2 2445.36   101.7 2445.53   110.8 2447.47   123.3 2447.53
   135.8 2446.79   148.2 2446.75   153.5 2446.16   160.7 2444.43   164.9 2444.08
     169 2444.55   173.2 2447.34   177.3 2450.51   181.5 2452.17   185.6 2452.41
     194 2452.14   198.1 2452.41   202.3 2453.15   206.4 2454.82   212.8  2458.2
#Mann= 4 ,-1,0
       0     .05       0      20      .1       0    80.8    .045       0
   92.58      .1       0
#XS Ineff= 2 , 0
                          148.55         2453.72
Permanent Ineff=
       F       F
Bank Sta=80.8,92.58
XS Rating Curve= 0 ,0
Exp/Cntr(USF)=0,0
Exp/Cntr=0.3,0.1

Type RM Length L Ch R = 1 ,3681    ,114,109.5,104.3
XS GIS Cut Line= 2
2262405.59064388 498746.025929792262499.25306379498516.776006762
#Sta/Elev= 30
       0    2463     9.6 2460.56    11.8 2459.74    13.9 2458.92      18  2456.2
    22.5 2451.25    26.8 2445.71    31.2 2441.46    42.5 2439.54    48.4 2439.05
    52.8 2439.03    57.1 2439.14    60.3 2439.87    65.7 2441.55    67.1  2441.7
    78.7 2441.48    91.7 2441.66      96 2442.31   100.3 2443.65   104.6 2444.49
   131.5 2444.57   159.1 2445.41   182.4 2445.36   208.3 2446.69     217 2446.36
   221.3 2446.51   225.6 2447.12   238.6 2451.22   242.9 2452.82   247.6 2455.01
#Mann= 4 ,-1,0
       0     .05       0    42.5    .045       0    60.3     .05       0
     230      .1       0
Bank Sta=42.5,60.3
XS Rating Curve= 0 ,0
Exp/Cntr(USF)=0,0
Exp/Cntr=0.3,0.1

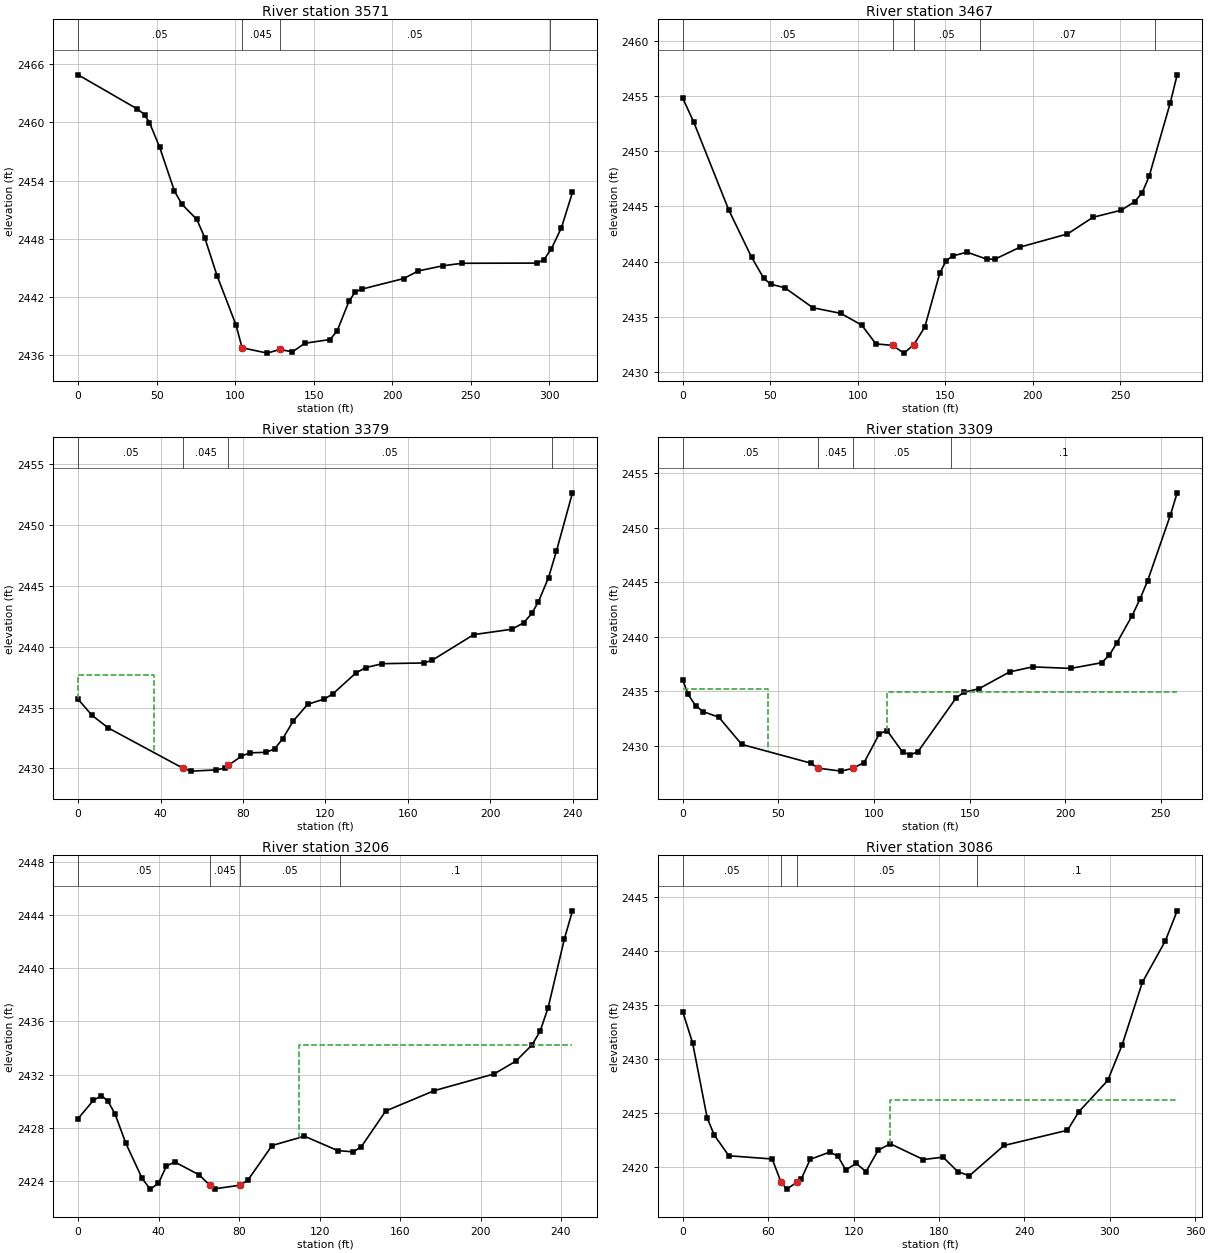
Type RM Length L Ch R = 1 ,3571    ,108.7,104.5,103
XS GIS Cut Line= 3
2262485.14883022498816.8219778572262528.62383497498748.973871271
2262537.31039209498515.031159783
#Sta/Elev= 30
       0 2464.88    37.6 2461.37    42.3 2460.79    45.4 2459.96    51.8 2457.47
    61.3 2452.92    66.1 2451.55    75.6 2449.99    80.6 2448.11    88.4 2444.22
   100.4 2439.17   104.4 2436.78   120.4 2436.23   128.4 2436.61   136.4 2436.36
   144.4 2437.25   160.4 2437.63   164.9 2438.52   172.4 2441.56   176.4 2442.53
   180.4 2442.81   207.3 2443.91   216.5 2444.69   232.5 2445.23   244.5 2445.48
   292.2  2445.5   296.5 2445.84   301.2 2446.95   307.7 2449.15   314.7 2452.78
#Mann= 4 ,-1,0
       0     .05       0   104.4    .045       0   128.4     .05       0
  300.58      .1       0
Bank Sta=104.4,128.4
XS Rating Curve= 0 ,0
Exp/Cntr(USF)=0,0
Exp/Cntr=0.3,0.1

Type RM Length L Ch R = 1 ,3467    ,88.2,87.9,88.6
XS GIS Cut Line= 2
  2262617.466367 498799.401203622262629.48857228498517.119823657
#Sta/Elev= 30
       0 2454.79     6.2 2452.65    26.2  2444.7    39.3  2440.4    46.3 2438.48
    50.3 2437.96    58.3 2437.64    74.3 2435.83    90.3 2435.32   102.3 2434.25
   110.3 2432.56   119.9 2432.42   126.3 2431.72  131.932432.465   138.3 2434.09
   146.8 2438.94   150.4 2440.09   154.2 2440.52   162.4 2440.86   173.7 2440.23
   178.4 2440.23   192.9 2441.33   219.8 2442.51   234.4 2444.02   250.5 2444.66
   258.2 2445.43   262.5 2446.24   266.5 2447.74   278.5 2454.35   282.5 2456.92
#Mann= 5 ,-1,0
       0     .05       0   119.9    .045       0  131.93     .05       0
     170     .07       0     270      .1       0
Bank Sta=119.9,131.93
XS Rating Curve= 0 ,0
Exp/Cntr(USF)=0,0
Exp/Cntr=0.3,0.1

Type RM Length L Ch R = 1 ,3379    ,71.4,69.8,68.8
XS GIS Cut Line= 2
2262700.77557751498755.811024255  2262729.320315 498517.64087076
#Sta/Elev= 30
       0 2435.68     6.7 2434.37    14.7 2433.32      51 2430.01      55 2429.78
    67.1 2429.88    71.1 2430.03    72.82430.246    79.2    2431    83.2 2431.28
    91.3 2431.33    95.4 2431.61    99.3 2432.45   104.4  2433.9   111.4 2435.27
   119.5 2435.71   123.5 2436.11   134.9 2437.86   139.6 2438.29   147.7 2438.61
   167.8 2438.67   171.9  2438.9     192    2441   210.5 2441.44   216.2 2441.97
   220.2 2442.74   223.4 2443.71   228.3 2445.69   232.1 2447.85   239.9 2452.65
#Mann= 4 ,-1,0
       0     .05       0      51    .045       0    72.8     .05       0
     230      .1       0
#XS Ineff= 2 , 0
           37.04 2437.71
Permanent Ineff=
       F       F
Bank Sta=51,72.8
XS Rating Curve= 0 ,0
Exp/Cntr(USF)=0,0
Exp/Cntr=0.3,0.1

Type RM Length L Ch R = 1 ,3309    ,102.2,103,104
XS GIS Cut Line= 2
2262774.42247455498771.9088151672262786.44467983498513.671845764
#Sta/Elev= 30
       0 2436.03     2.7 2434.71     6.7 2433.66    10.7 2433.12    18.8 2432.62
    30.8 2430.12    66.8 2428.41    70.8 2427.94    82.8 2427.67   88.952427.934
    94.8 2428.46   102.8  2431.1   106.8 2431.39   114.9 2429.42   118.9 2429.17
   122.9 2429.44   142.9 2434.38   146.9 2434.89   154.9 2435.23   170.9 2436.77
   182.9 2437.23   202.9 2437.09     219 2437.61     223  2438.3     227 2439.44
     235 2441.94     239 2443.43     243  2445.1     255 2451.17   258.5 2453.19
#Mann= 4 ,-1,0
       0     .05       0    70.8    .045       0   88.95     .05       0
     140      .1       0
#XS Ineff= 2 , 0
           44.44 2435.16  106.76         2434.89
Permanent Ineff=
       F       F
Bank Sta=70.8,88.95
XS Rating Curve= 0 ,0
Exp/Cntr(USF)=0,0
Exp/Cntr=0.3,0.1

Type RM Length L Ch R = 1 ,3206    ,114.1,120.4,126.8
XS GIS Cut Line= 2
2262871.15197945498756.7030473022262904.15683218498513.180755526
#Sta/Elev= 30
       0 2428.69     7.6 2430.06    11.6  2430.4    14.7 2430.02    18.3 2429.05
    23.7 2426.83    31.8 2424.19    35.8 2423.38    39.9 2423.81    43.9 2425.12
      48 2425.42    60.1 2424.46    65.52423.663    68.1 2423.41    80.3 2423.67
    84.3 2424.04    96.4 2426.66   112.5 2427.36     129 2426.28   136.8 2426.18
   140.8 2426.58   152.9 2429.26   177.1 2430.79   206.7 2432.04   217.5    2433
   225.6 2434.22   229.6 2435.25   233.6 2437.02   241.7 2442.21   245.7 2444.31
#Mann= 4 ,-1,0
       0     .05       0    65.5    .045       0    80.3     .05       0
     130      .1       0
#XS Ineff= 2 , 0
                          109.94          2434.2
Permanent Ineff=
       F       F
Bank Sta=65.5,80.3
XS Rating Curve= 0 ,0
Exp/Cntr(USF)=0,0
Exp/Cntr=0.3,0.1

Type RM Length L Ch R = 1 ,3086    ,91.1,78.2,67.9
XS GIS Cut Line= 3
2262936.86434389498802.5926773762263027.47842372498687.292057961
2262996.16290334498489.010722233
#Sta/Elev= 30
       0 2434.32     6.9 2431.44    17.1 2424.52    22.1 2422.92    32.3 2421.01
    62.8 2420.71    68.9  2418.6      73 2417.92   80.072418.544    83.1 2418.82
    89.5 2420.68   103.1 2421.34   108.8    2421   114.5  2419.7   121.9  2420.3
   128.7 2419.54   137.3 2421.52   145.8 2422.12     169 2420.66   182.9 2420.88
   193.3 2419.53   201.4 2419.16   225.7 2421.96   270.3 2423.37   278.4  2425.1
   298.6 2427.98   308.8  2431.3   322.9 2437.06   339.1 2440.91   347.4 2443.69
#Mann= 4 ,-1,0
       0     .05       0    68.9    .045       0   80.07     .05       0
  206.65      .1       0
#XS Ineff= 2 , 0
                          145.41         2426.17
Permanent Ineff=
       F       F
Bank Sta=68.9,80.07
XS Rating Curve= 0 ,0
Exp/Cntr(USF)=0,0
Exp/Cntr=0.3,0.1