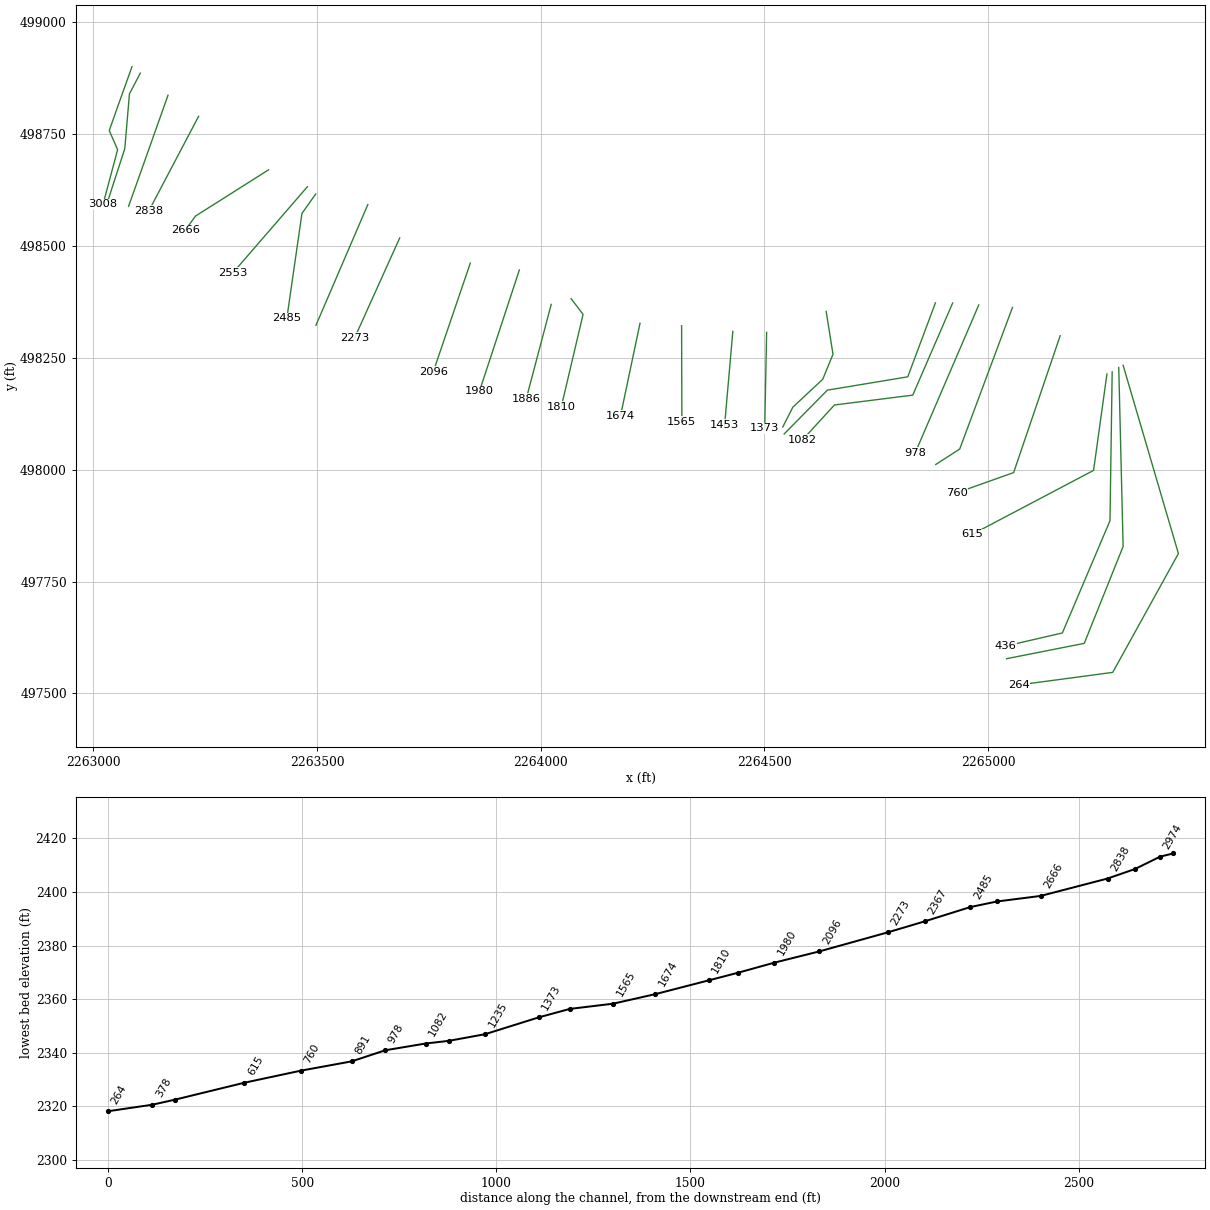
HEC-RAS study ELKLCKRN1.prj: ELKLCKRN1

--- ELKLCKRN1.g01 (geometry) --- (continued)

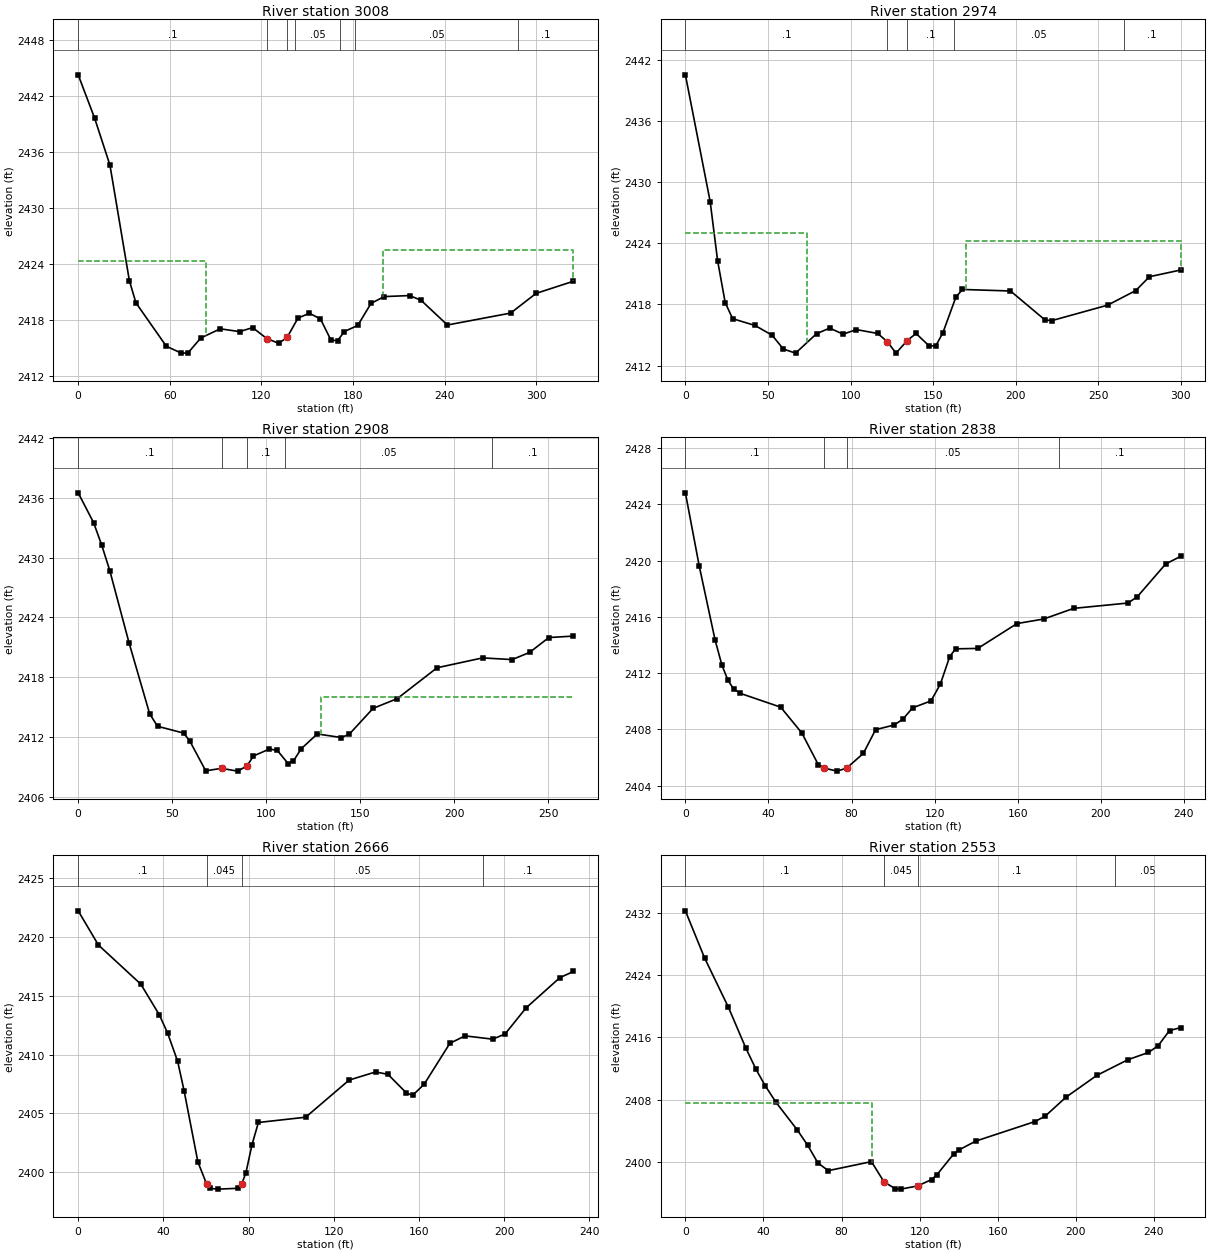
Type RM Length L Ch R = 1 ,3008    ,31.8,34,37.2
XS GIS Cut Line= 5
2263086.35839429498900.7447607482263055.36782069498814.184882736
  2263035.597972498758.0812580982263054.29918022498715.335639327
 2263021.7056459498593.510625828
#Sta/Elev= 30
       0 2444.29    10.8 2439.62    20.8 2434.59    33.5  2422.2    37.8 2419.81
    57.7 2415.15    67.5 2414.41    71.8 2414.42    80.3 2416.04      93 2417.02
   105.7 2416.72   114.2 2417.15   123.5 2415.97   131.2 2415.47  136.76 2416.09
   143.9 2418.18   151.4 2418.69   158.6 2418.08   165.5 2415.79   169.9 2415.76
   174.2 2416.73     183 2417.38   191.7 2419.75   200.3 2420.48   216.9 2420.59
   224.4 2420.09   241.7 2417.43   283.1 2418.71   299.7 2420.82   324.2 2422.13
#Mann= 7 ,-1,0
       0      .1       0   123.5    .045       0  136.76      .1       0
  141.94     .05       0  171.43      .1       0  181.43     .05       0
  288.08      .1       0
#XS Ineff= 2 , 0
           83.41 2424.34  199.48         2425.51
Permanent Ineff=
       F       F
Bank Sta=123.5,136.76
XS Rating Curve= 0 ,0
Exp/Cntr(USF)=0,0
Exp/Cntr=0.3,0.1

Type RM Length L Ch R = 1 ,2974    ,68.7,65.4,62.6
XS GIS Cut Line= 4
2263104.95968815498886.5129239622263080.71662347 498839.99606108
2263070.28966008498717.5891088732263031.82866897498599.132061947
#Sta/Elev= 30
       0 2440.54      15  2428.1    19.5  2422.3    24.1 2418.18    28.6  2416.6
    42.1 2415.94    52.5 2414.98    59.3 2413.62    66.7 2413.22    79.4 2415.13
    87.4 2415.68    95.4 2415.08   103.5 2415.53   116.4 2415.15   122.2 2414.35
   127.5 2413.22  134.312414.457   139.6 2415.15   147.6 2413.92   151.6 2413.94
   155.9 2415.23   163.7  2418.7   167.7 2419.47   196.8 2419.32   217.8 2416.46
     222 2416.42   255.6 2417.93   272.6 2419.36   280.9 2420.72   299.8 2421.38
#Mann= 5 ,-1,0
       0      .1       0   122.2    .045       0  134.31      .1       0
  162.46     .05       0  265.31      .1       0
#XS Ineff= 2 , 0
           73.43 2425.02  169.58         2424.25
Permanent Ineff=
       F       F
Bank Sta=122.2,134.31
XS Rating Curve= 0 ,0
Exp/Cntr(USF)=0,0
Exp/Cntr=0.3,0.1

Type RM Length L Ch R = 1 ,2908    ,72.4,70.4,69
XS GIS Cut Line= 2
2263166.90500157498836.9753467262263078.81704617498588.849731905
#Sta/Elev= 30
       0 2436.49     8.2  2433.5    12.5 2431.25    16.8 2428.69      27 2421.47
      38 2414.32    42.2 2413.07      56 2412.39    59.2 2411.64    67.8  2408.6
    76.2 2408.85    84.7 2408.57    89.7 2409.08    93.2 2410.09   101.7 2410.79
   105.9 2410.64   111.6 2409.33   114.4 2409.58   118.6 2410.82   127.1  2412.3
   139.9 2411.94   144.1 2412.27   156.8 2414.87   169.6 2415.84   190.8 2418.94
     215 2419.93   230.7 2419.76     240 2420.48   250.2 2421.97   263.3 2422.12
#Mann= 5 ,-1,0
       0      .1       0    76.2    .045       0    89.7      .1       0
     110     .05       0     220      .1       0
#XS Ineff= 2 , 0
                          129.22         2415.99
Permanent Ineff=
       F       F
Bank Sta=76.2,89.7
XS Rating Curve= 0 ,0
Exp/Cntr(USF)=0,0
Exp/Cntr=0.3,0.1

Type RM Length L Ch R = 1 ,2838    ,178,172.1,164.8
XS GIS Cut Line= 2
2263235.29560988498789.8070137062263124.19347993498578.768053907
#Sta/Elev= 30
       0 2424.83     6.7  2419.6    14.3 2414.36    17.6 2412.57    20.5 2411.49
    23.3 2410.86    26.5 2410.56    45.9 2409.58    56.1 2407.74      64 2405.49
    66.8 2405.25      73 2405.03    77.6 2405.24    85.7 2406.29    91.6 2407.98
   100.5 2408.31   104.7 2408.72   109.4 2409.53   118.3 2410.03   122.8 2411.23
   127.3 2413.18   130.1 2413.73   140.8 2413.76   159.7 2415.53   172.5 2415.85
     187 2416.61   213.2 2416.99   217.7 2417.45   231.3 2419.77   238.5 2420.31
#Mann= 4 ,-1,0
       0      .1       0    66.8    .045       0    77.6     .05       0
     180      .1       0
Bank Sta=66.8,77.6
XS Rating Curve= 0 ,0
Exp/Cntr(USF)=0,0
Exp/Cntr=0.3,0.1

Type RM Length L Ch R = 1 ,2666    ,107.9,112.3,116.2
XS GIS Cut Line= 3
2263391.65099535498670.261553952 2263228.3572564498566.938524441
2263205.31693279498535.158336475
#Sta/Elev= 30
       0 2422.23     9.5 2419.32    29.4 2415.99    38.1 2413.38      42 2411.82
    46.7 2409.42    49.7 2406.94    56.2 2400.86   60.382398.948    61.9 2398.61
    65.6 2398.55    75.1 2398.62    76.8 2399.02    78.7 2399.91    81.6 2402.33
    84.6 2404.22   106.8 2404.67   127.2 2407.83   139.6 2408.52   145.4 2408.32
   154.1 2406.73     157 2406.53   162.4 2407.47   174.5 2410.96   181.6 2411.59
   194.6 2411.31   200.4 2411.75   210.2 2413.96   226.1 2416.54   232.5 2417.07
#Mann= 4 ,-1,0
       0      .1       0   60.38    .045       0    76.8     .05       0
     190      .1       0
Bank Sta=60.38,76.8
XS Rating Curve= 0 ,0
Exp/Cntr(USF)=0,0
Exp/Cntr=0.3,0.1

Type RM Length L Ch R = 1 ,2553    ,59.9,68.8,77.3
XS GIS Cut Line= 2
2263478.55391872 498632.559294912263312.59526141498440.728755656
#Sta/Elev= 30
       0  2432.3     9.8 2426.25      22 2419.91    30.9 2414.67    36.2 2411.89
    40.9 2409.78    46.4 2407.66    57.4 2404.07    62.7  2402.1    67.9 2399.84
    73.2 2398.86    95.3 2400.02   101.82397.394   107.6 2396.53   110.3 2396.48
     1192396.891   126.1 2397.71   128.9 2398.35   137.4    2401   140.2 2401.53
   148.7 2402.66     179 2405.17   184.3 2405.87   194.9  2408.3   210.7 2411.11
   226.6 2413.13   237.2 2414.07   242.1 2414.92     248 2416.89   253.7 2417.27
#Mann= 4 ,-1,0
       0      .1       0   101.8    .045       0     119      .1       0
     220     .05       0
#XS Ineff= 2 , 0
           95.65 2407.61
Permanent Ineff=
       F       F
Bank Sta=101.8,119
XS Rating Curve= 0 ,0
Exp/Cntr(USF)=0,0
Exp/Cntr=0.3,0.1

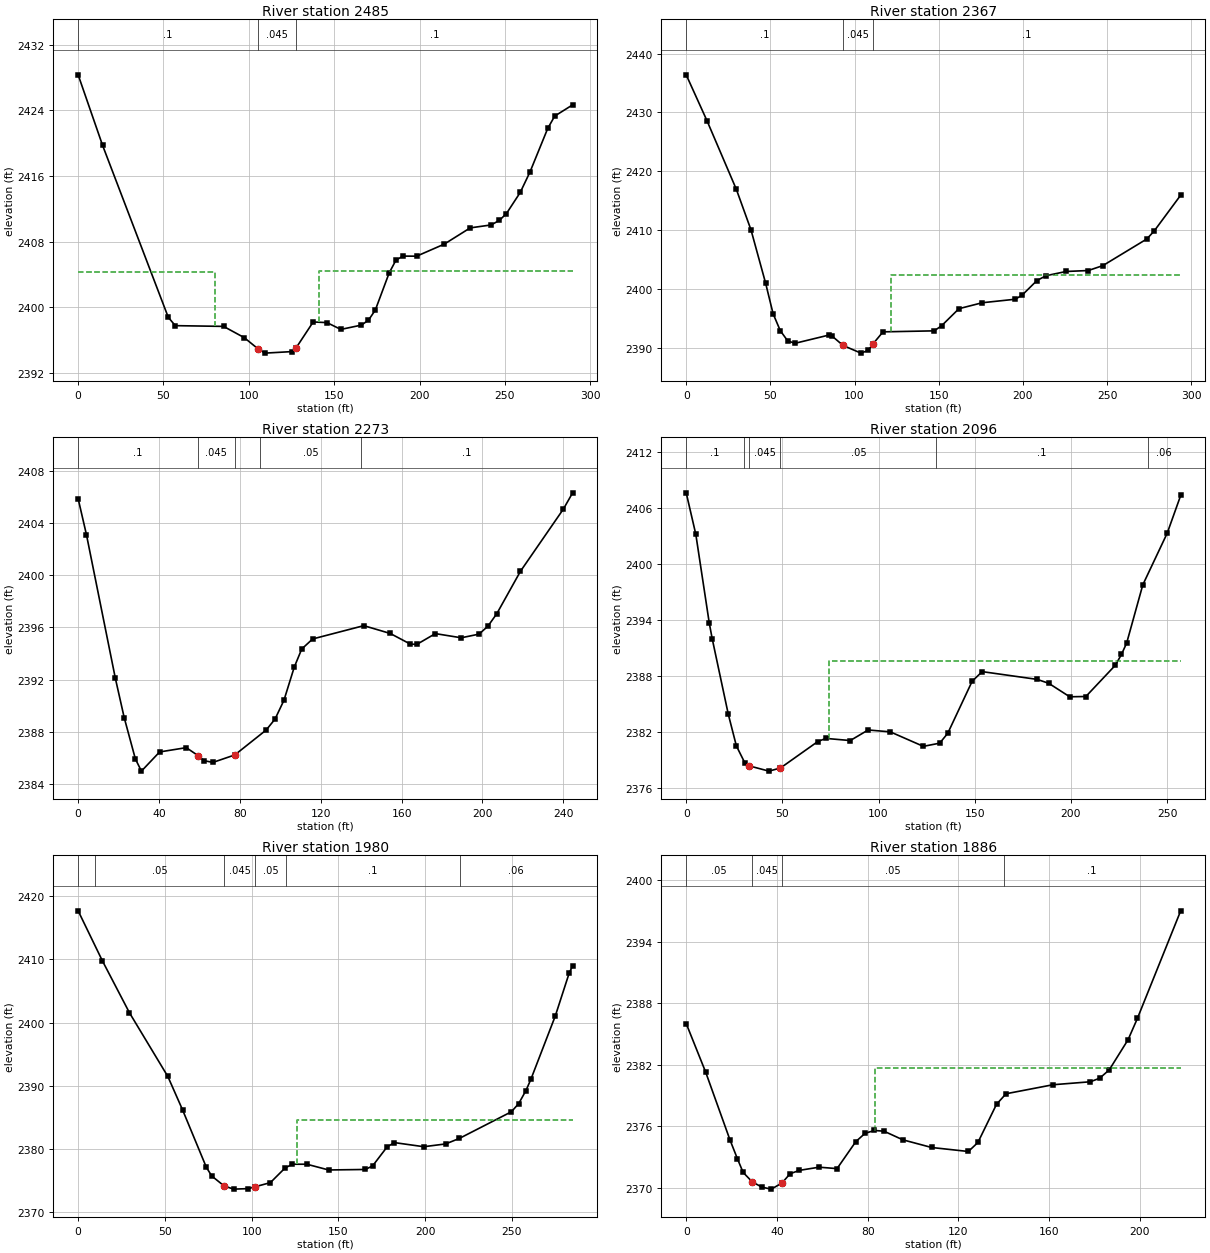
Type RM Length L Ch R = 1 ,2485    ,121.2,117.6,114.4
XS GIS Cut Line= 3
2263497.03602974498616.3072646512263466.31079146498572.697249029
2263432.61214302498338.788983424
#Sta/Elev= 30
       0 2428.33    14.3 2419.74    52.8 2398.77    56.9 2397.75    85.2 2397.66
    97.3 2396.29   105.4 2394.92   109.4  2394.4   125.5 2394.59  127.582395.005
   137.7  2398.2   145.8 2398.12   153.9 2397.29     166 2397.82   170.1 2398.42
   174.1 2399.65   182.2 2404.17   186.2 2405.74   190.3 2406.23   198.3 2406.22
   214.5 2407.69   229.7 2409.67     242 2410.03   246.8 2410.59   250.9 2411.41
     259 2413.99   264.7 2416.48   275.1 2421.79   279.2  2423.3   289.7 2424.67
#Mann= 3 ,-1,0
       0      .1       0   105.4    .045       0  127.58      .1       0
#XS Ineff= 2 , 0
           80.42 2404.27  140.96         2404.47
Permanent Ineff=
       F       F
Bank Sta=105.4,127.58
XS Rating Curve= 0 ,0
Exp/Cntr(USF)=0,0
Exp/Cntr=0.3,0.1

Type RM Length L Ch R = 1 ,2367    ,94.7,94.3,94.1
XS GIS Cut Line= 2
2263613.56132066498592.5533806232263497.61382974498322.721662128
#Sta/Elev= 30
       0  2436.4    12.4 2428.56    29.8 2416.91    38.5 2410.01    47.2 2400.93
    51.6 2395.77    55.9 2392.87    60.3 2391.14    64.6 2390.73    84.6 2392.12
    86.4 2392.02    93.2 2390.36   103.8 2389.06   108.2 2389.53   110.72390.547
   116.9 2392.68   147.3 2392.85   151.7 2393.72     162 2396.62   175.8 2397.63
   195.5 2398.23   199.6 2398.95   208.3  2401.4   213.7 2402.23   225.7 2402.95
   238.8 2403.11   247.5 2403.95   273.6 2408.48     278 2409.85   293.7 2415.93
#Mann= 3 ,-1,0
       0      .1       0    93.2    .045       0   110.7      .1       0
#XS Ineff= 2 , 0
                          121.74         2402.38
Permanent Ineff=
       F       F
Bank Sta=93.2,110.7
XS Rating Curve= 0 ,0
Exp/Cntr(USF)=0,0
Exp/Cntr=0.3,0.1

Type RM Length L Ch R = 1 ,2273    ,175.7,177.1,178.7
XS GIS Cut Line= 2
2263684.83460876498517.9498517352263584.22539452498294.978079635
#Sta/Elev= 30
       0 2405.87     4.1 2403.12    18.4 2392.11    22.8 2389.08    28.3 2385.93
    31.3 2384.99    40.3 2386.46    53.5 2386.79    59.3 2386.18    62.3 2385.79
    66.7 2385.66    77.52386.232      93 2388.14    97.4 2388.98   101.8 2390.42
   106.9 2392.96   110.6 2394.35     116 2395.12   141.3 2396.14   154.4 2395.54
   164.4 2394.72   167.6 2394.71   176.7 2395.53   189.5 2395.21   198.3 2395.49
   202.7  2396.1   207.1 2397.06   218.8 2400.31     240 2405.07   244.6 2406.32
#Mann= 5 ,-1,0
       0      .1       0    59.3    .045       0    77.5      .1       0
      90     .05       0     140      .1       0
Bank Sta=59.3,77.5
XS Rating Curve= 0 ,0
Exp/Cntr(USF)=0,0
Exp/Cntr=0.3,0.1

Type RM Length L Ch R = 1 ,2096    ,115.9,115.7,116.7
XS GIS Cut Line= 2
2263842.69565613498461.9142858452263759.76103358498218.548754101
#Sta/Elev= 30
       0 2407.61       5 2403.17      12 2393.68    13.5 2392.03    21.9 2383.92
    26.1 2380.54    30.4 2378.77    32.6 2378.42      43 2377.85   48.992378.182
    68.4 2381.01    72.6 2381.35    85.3 2381.12    94.6 2382.25   106.1 2382.05
   123.3  2380.5   131.8 2380.84     136  2381.9   148.7 2387.47   153.9 2388.49
   182.5 2387.66   188.5 2387.24   199.4  2385.8   207.8 2385.83   223.2 2389.19
   226.3 2390.33     229 2391.54   237.4 2397.77   250.1  2403.3   257.1 2407.33
#Mann= 6 ,-1,0
       0      .1       0      30     .05       0    32.6    .045       0
   48.99     .05       0     130      .1       0     240     .06       0
#XS Ineff= 2 , 0
                            74.4         2389.59
Permanent Ineff=
       F       F
Bank Sta=32.6,48.99
XS Rating Curve= 0 ,0
Exp/Cntr(USF)=0,0
Exp/Cntr=0.3,0.1

Type RM Length L Ch R = 1 ,1980    ,93.5,94.2,95.2
XS GIS Cut Line= 2
2263952.27649008498446.3916725652263863.22311764498175.669420345
#Sta/Elev= 30
       0 2417.69    13.9 2409.82    29.6 2401.55    51.7 2391.48    60.2 2386.19
    73.9 2377.11      77 2375.74    84.22374.145    89.7 2373.66    98.1 2373.74
   102.1 2374.04   110.8 2374.69   119.2 2376.99   123.4  2377.6   131.8  2377.6
   144.4 2376.69   165.5 2376.77   169.7 2377.33   178.1 2380.35   182.3 2381.02
   199.2 2380.37   211.8 2380.81   219.7 2381.68   249.7  2385.9   253.9 2387.19
   258.1 2389.26   260.9 2391.01     275 2401.05     283 2407.83     285    2409
#Mann= 6 ,-1,0
       0      .1       0      10     .05       0    84.2    .045       0
   102.1     .05       0     120      .1       0     220     .06       0
#XS Ineff= 2 , 0
                          126.09         2384.62
Permanent Ineff=
       F       F
Bank Sta=84.2,102.1
XS Rating Curve= 0 ,0
Exp/Cntr(USF)=0,0
Exp/Cntr=0.3,0.1

Type RM Length L Ch R = 1 ,1886    ,75.2,75.5,75.8
XS GIS Cut Line= 2
2264023.52032497498369.4625754622263967.77738194498158.727059148
#Sta/Elev= 30
       0 2386.02     8.6 2381.27    19.3 2374.67    22.6 2372.82    25.1  2371.5
    29.1 2370.58    33.4 2370.06    37.5 2369.87    42.2 2370.46    45.8 2371.37
    49.9  2371.7    58.6 2372.01    66.5 2371.87    74.8 2374.51    78.9 2375.32
      83 2375.59    87.2 2375.52    95.5 2374.68   108.2 2373.93   124.4 2373.54
   128.6 2374.42   136.8 2378.14     141 2379.17   161.7 2380.05   178.2 2380.34
   182.3 2380.69   186.5  2381.5   194.8 2384.44   198.9 2386.51     218 2397.01
#Mann= 4 ,-1,0
       0     .05       0    29.1    .045       0    42.2     .05       0
     140      .1       0
#XS Ineff= 2 , 0
                           83.33         2381.71
Permanent Ineff=
       F       F
Bank Sta=29.1,42.2
XS Rating Curve= 0 ,0
Exp/Cntr(USF)=0,0
Exp/Cntr=0.3,0.1

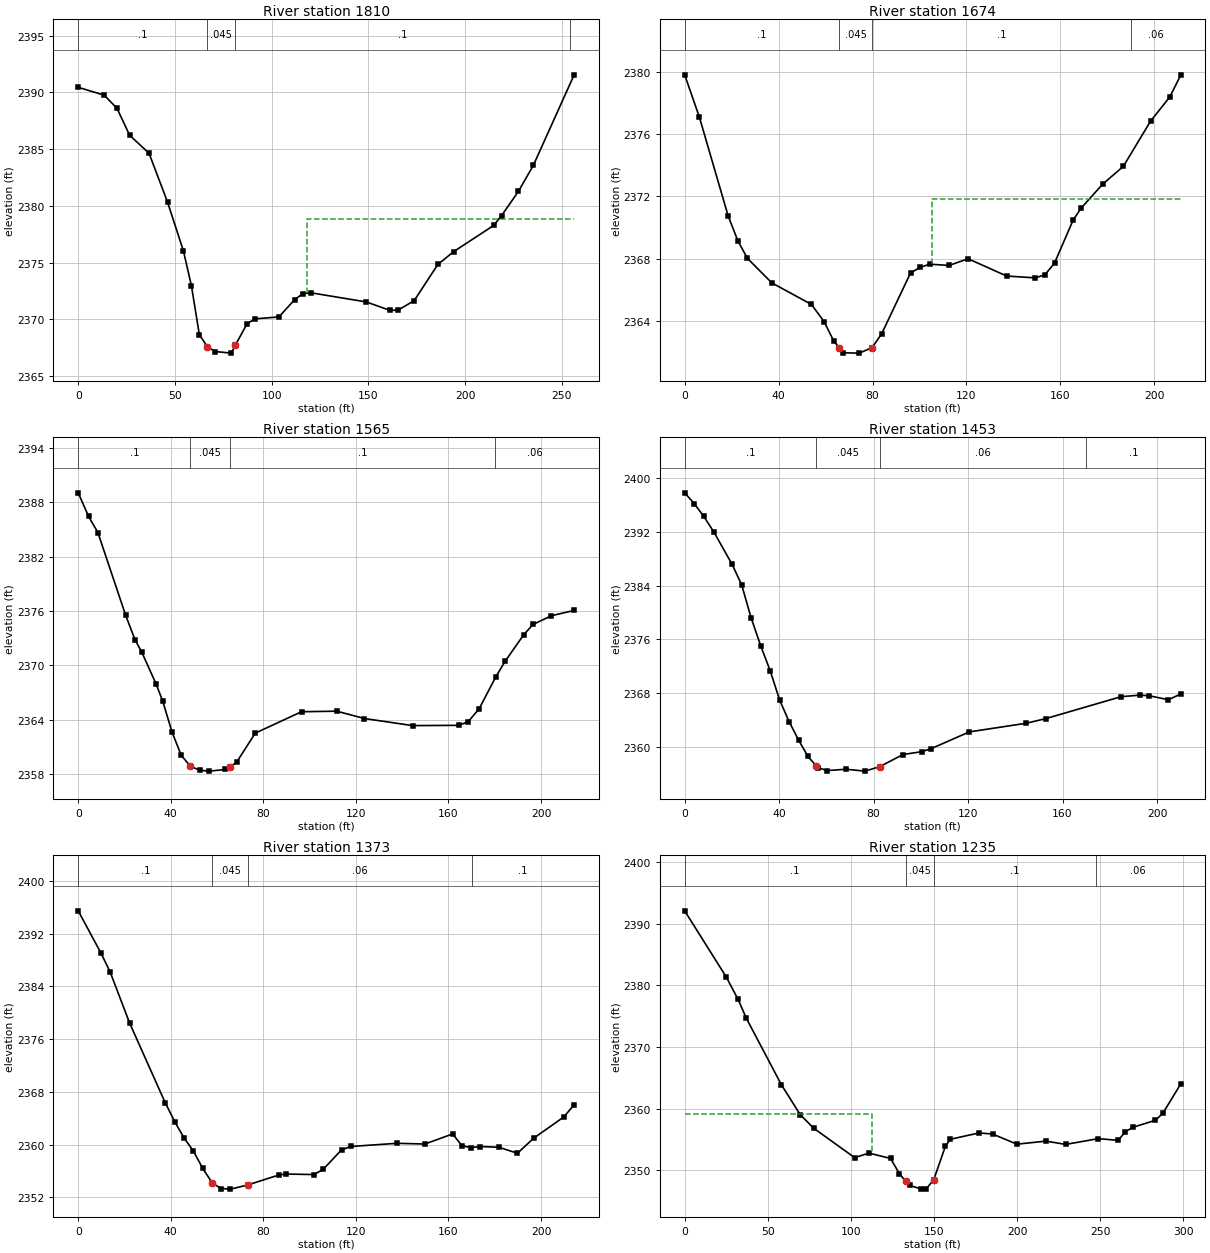
Type RM Length L Ch R = 1 ,1810    ,136.1,136.6,136.6
XS GIS Cut Line= 3
2264068.04587425498382.2732444082264094.76188598498347.245584581
2264046.07937572498140.641760519
#Sta/Elev= 30
       0 2390.45    13.4 2389.76      20 2388.61    26.6 2386.22    36.6 2384.64
    46.2 2380.32    54.4 2376.02    58.5 2372.97    62.6 2368.66    66.8 2367.58
    70.8 2367.17    79.1 2367.03    81.2 2367.73    87.3 2369.63    91.4 2370.05
   103.7 2370.22   111.9 2371.75     116 2372.26   120.1 2372.35   148.9 2371.54
   161.2 2370.79   165.4 2370.83   173.6 2371.65   185.9 2374.85   194.1 2375.98
   214.7 2378.28   218.8 2379.15   227.5 2381.28   235.2 2383.57   256.3 2391.55
#Mann= 4 ,-1,0
       0      .1       0    66.8    .045       0    81.2      .1       0
  254.05     .06       0
#XS Ineff= 2 , 0
                          118.36         2378.87
Permanent Ineff=
       F       F
Bank Sta=66.8,81.2
XS Rating Curve= 0 ,0
Exp/Cntr(USF)=0,0
Exp/Cntr=0.3,0.1

Type RM Length L Ch R = 1 ,1674    ,106.7,109.1,111.5
XS GIS Cut Line= 2
 2264222.0195855498327.3154721992264178.51289826498120.658707813
#Sta/Elev= 30
       0 2379.82     6.3 2377.08    18.5 2370.75    22.6 2369.16    26.7 2368.02
    37.1 2366.44      54 2365.05    59.4 2363.94    63.5 2362.69    65.82362.267
    67.6 2361.94    74.3 2361.92    79.8 2362.27    83.9 2363.17    96.2 2367.08
   100.3 2367.44   104.4 2367.64   112.6 2367.56   120.7 2367.99   137.1 2366.88
   149.3 2366.76   153.4 2366.96   157.5 2367.71   165.4 2370.47   168.8 2371.24
     178 2372.79   186.8 2373.93   198.4 2376.84   206.6  2378.4   211.2 2379.79
#Mann= 4 ,-1,0
       0      .1       0    65.8    .045       0    79.8      .1       0
     190     .06       0
#XS Ineff= 2 , 0
                          105.17         2371.86
Permanent Ineff=
       F       F
Bank Sta=65.8,79.8
XS Rating Curve= 0 ,0
Exp/Cntr(USF)=0,0
Exp/Cntr=0.3,0.1

Type RM Length L Ch R = 1 ,1565    ,112.9,111.7,112
XS GIS Cut Line= 2
2264315.02056049498321.7169511482264315.61424964498107.395168141
#Sta/Elev= 30
       0 2389.04     4.5 2386.43     8.5 2384.66    20.5 2375.54    24.5 2372.86
    27.5 2371.45    33.6 2367.99    36.5 2366.08    40.5 2362.69    44.5  2360.1
    48.5 2358.88    52.5 2358.45    56.5 2358.35    63.6 2358.53    65.5 2358.79
    68.5 2359.35    76.5 2362.54    96.5  2364.9   111.7 2364.96   123.7 2364.15
   144.5 2363.37   164.5  2363.4   168.5  2363.8   173.2 2365.21   180.5 2368.77
   184.5 2370.47   192.5 2373.39   196.5 2374.52   204.5 2375.49   214.3 2376.07
#Mann= 4 ,-1,0
       0      .1       0    48.5    .045       0    65.5      .1       0
     180     .06       0
Bank Sta=48.5,65.5
XS Rating Curve= 0 ,0
Exp/Cntr(USF)=0,0
Exp/Cntr=0.3,0.1

Type RM Length L Ch R = 1 ,1453    ,79.1,79.9,81.9
XS GIS Cut Line= 2
2264429.53288779498309.2194094762264411.17850411498099.979435535
#Sta/Elev= 30
       0 2397.84     4.1 2396.21     8.1 2394.32    12.4 2391.98    20.1 2387.17
    24.1 2384.17    28.1 2379.26    32.2 2375.04    36.2 2371.35    40.2 2366.99
    44.2 2363.77    48.2 2361.04    52.2 2358.57    55.8 2357.14    56.3 2356.93
    60.3 2356.47    68.3 2356.67    76.3 2356.39    82.5 2357.04    92.4 2358.86
   100.4 2359.29   104.4 2359.74   120.5 2362.23   144.6 2363.52   152.9 2364.21
   184.7 2367.47   192.8 2367.71   196.8 2367.61   204.8 2367.02     210 2367.87
#Mann= 4 ,-1,0
       0      .1       0    55.8    .045       0    82.5     .06       0
     170      .1       0
Bank Sta=55.8,82.5
XS Rating Curve= 0 ,0
Exp/Cntr(USF)=0,0
Exp/Cntr=0.3,0.1

Type RM Length L Ch R = 1 ,1373    ,141.8,137.9,132
XS GIS Cut Line= 2
2264505.06045728498306.934091323 2264500.7858954498092.671677231
#Sta/Elev= 30
       0 2395.45     9.8 2389.06    13.8 2386.17    22.2 2378.44    37.6 2366.34
    41.8  2363.4    45.8 2360.97    49.8    2359    53.8 2356.38      58 2354.14
    61.8 2353.33    65.8 2353.24    73.2 2353.87    86.6 2355.37    89.8 2355.53
   101.8 2355.45   105.8 2356.22   113.8  2359.2   117.8 2359.71   137.8 2360.19
   149.8 2360.08   161.8 2361.61   165.8 2359.83   169.8 2359.54   173.8  2359.7
   181.8 2359.59   189.8 2358.68   196.8 2360.96   209.8 2364.18   214.3 2366.02
#Mann= 4 ,-1,0
       0      .1       0      58    .045       0    73.2     .06       0
     170      .1       0
Bank Sta=58,73.2
XS Rating Curve= 0 ,0
Exp/Cntr(USF)=0,0
Exp/Cntr=0.3,0.1

Type RM Length L Ch R = 1 ,1235    ,107.9,93.8,61
XS GIS Cut Line= 5
2264638.19614457498353.7980568012264653.41677039498258.032120682
2264630.52116348498202.1819636332264563.68940023498139.762732235
2264541.21435197 498095.61566719
#Sta/Elev= 30
       0 2392.11    24.9 2381.42    32.1 2377.77    37.1 2374.67    58.2 2363.89
    69.5 2359.05    77.6 2356.85   102.2 2352.08   110.9 2352.81   123.8 2351.95
   129.2 2349.46   132.9 2348.24   135.4 2347.57   142.4 2346.97   145.4 2347.05
   149.8 2348.49   156.8 2353.91   159.7 2355.05     177 2356.08   185.2 2355.91
   199.8 2354.26   217.4 2354.76   229.1 2354.22   248.8 2355.16   260.7 2354.88
   265.1 2356.28   269.6    2357   283.1 2358.13   287.6 2359.27   298.3    2364
#Mann= 4 ,-1,0
       0      .1       0   132.9    .045       0   149.8      .1       0
  247.33     .06       0
#XS Ineff= 2 , 0
          112.56 2359.23
Permanent Ineff=
       F       F
Bank Sta=132.9,149.8
XS Rating Curve= 0 ,0
Exp/Cntr(USF)=0,0
Exp/Cntr=0.5,0.3

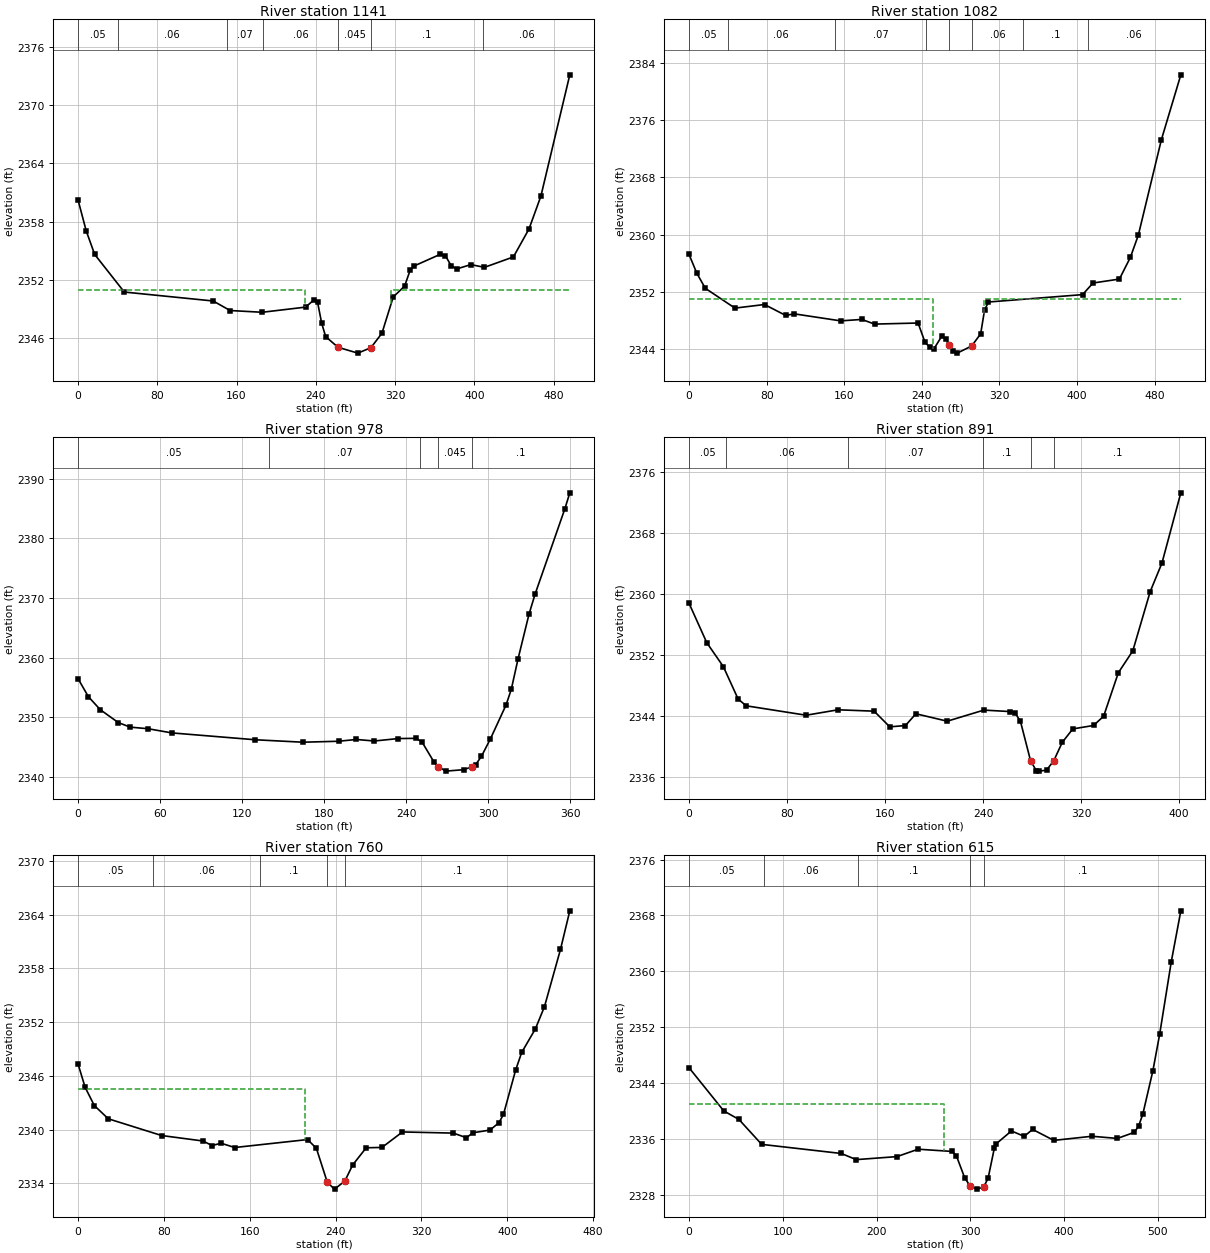
Type RM Length L Ch R = 1 ,1141    ,62.2,59.4,73.2
XS GIS Cut Line= 4
2264882.39671443498372.9567062812264820.56283519498207.604103093
2264640.77145017498177.7612348152264544.24098786498079.871188527
#Sta/Elev= 30
       0 2360.24     8.3 2357.04    16.8 2354.63    46.7 2350.76   136.4 2349.84
   153.5 2348.86   185.9 2348.68   229.6 2349.21   238.1 2349.95   241.8 2349.69
   245.9 2347.56   249.9 2346.18   262.4 2345.08   282.4 2344.48   295.6 2345.04
   306.7 2346.52   318.1 2350.25   329.6 2351.37   335.1 2352.98   339.4 2353.45
   365.2 2354.62   370.8 2354.49   376.5 2353.48   382.1 2353.13   396.4 2353.58
   410.2  2353.3   439.4 2354.37   455.1 2357.24   467.1 2360.61   496.3 2373.09
#Mann= 7 ,-1,0
       0     .05       0      40     .06       0     150     .07       0
  186.54     .06       0   262.4    .045       0   295.6      .1       0
  408.79     .06       0
#XS Ineff= 2 , 0
             229    2351     316            2351
Permanent Ineff=
       F       F
Bank Sta=262.4,295.6
XS Rating Curve= 0 ,0
Exp/Cntr(USF)=0,0
Exp/Cntr=0.5,0.3

Type RM Length L Ch R = 1 ,1082    ,86.8,104.2,122.1
XS GIS Cut Line= 4
2264920.94092015498372.6032144472264831.73861547498166.667029569
2264656.63779518498144.6417691542264585.05569883498066.452094681
#Sta/Elev= 30
       0 2357.26     8.1 2354.61    16.8 2352.53    47.3 2349.77    77.8 2350.27
    99.6 2348.75   108.4 2348.97   156.3 2347.99   178.1 2348.19   191.2 2347.54
   236.1 2347.69   243.3 2344.98   248.2 2344.32   252.2 2344.04   260.3 2345.81
   264.8  2345.5   268.3 2344.69   271.9 2343.74   276.4 2343.49   291.4 2344.49
   300.6 2346.19   304.6  2349.5   308.6 2350.62   405.6 2351.65   416.4 2353.27
   443.6 2353.82   454.9 2356.85   463.1 2359.95   486.9 2373.28   506.9 2382.31
#Mann= 8 ,-1,0
       0     .05       0      40     .06       0     150     .07       0
  244.43     .06       0   268.3    .045       0   291.4     .06       0
  344.43      .1       0  410.91     .06       0
#XS Ineff= 2 , 0
             251    2351     304            2351
Permanent Ineff=
       F       F
Bank Sta=268.3,291.4
XS Rating Curve= 0 ,0
Exp/Cntr(USF)=0,0
Exp/Cntr=0.5,0.3

Type RM Length L Ch R = 1 ,978     ,85.6,86.3,87.8
XS GIS Cut Line= 2
2264979.30786025498368.1981623642264837.24493058498037.819256142
#Sta/Elev= 30
       0 2356.47     7.6 2353.44    16.3 2351.26    29.4 2349.11    38.1 2348.34
    51.2 2348.07    68.6 2347.37   129.6 2346.22   164.4 2345.81   190.5 2345.97
   203.6 2346.27   216.6 2346.01   234.1 2346.42   247.1 2346.46   251.5 2345.86
   260.4 2342.45   263.5 2341.71   268.9 2340.96     282  2341.2   287.9 2341.68
   290.7 2342.03     295 2343.44   301.6 2346.39     313 2352.06   316.8 2354.66
   321.8 2359.82   329.8  2367.3   334.2 2370.63     356 2384.96   359.6 2387.63
#Mann= 5 ,-1,0
       0     .05       0     140     .07       0     250      .1       0
   263.5    .045       0   287.9      .1       0
Bank Sta=263.5,287.9
XS Rating Curve= 0 ,0
Exp/Cntr(USF)=0,0
Exp/Cntr=0.3,0.1

Type RM Length L Ch R = 1 ,891     ,131,131.6,132.4
XS GIS Cut Line= 3
 2265054.6612245498362.7291441932264936.65634415 498046.09493107
2264883.15102573498011.646301402
#Sta/Elev= 30
       0 2358.78    14.5 2353.62      28  2350.5    40.1 2346.25    46.7 2345.37
    95.6 2344.14   121.7 2344.85   151.1 2344.67   163.9 2342.62   176.7 2342.79
   185.2 2344.33   210.8 2343.36   240.7 2344.81     262 2344.62   266.3 2344.41
   270.6 2343.32   278.82338.207   283.4 2336.91   286.1 2336.83   291.9 2336.96
   297.8  2338.2   304.7 2340.59   313.3 2342.35   330.3  2342.8   338.5 2344.02
   350.5  2349.7   362.3 2352.56   376.5 2360.31   386.1 2364.04   401.5 2373.22
#Mann= 6 ,-1,0
       0     .05       0      30     .06       0     130     .07       0
     240      .1       0   278.8    .045       0   297.8      .1       0
Bank Sta=278.8,297.8
XS Rating Curve= 0 ,0
Exp/Cntr(USF)=0,0
Exp/Cntr=0.3,0.1

Type RM Length L Ch R = 1 ,760     ,154.9,144.8,135
XS GIS Cut Line= 3
2265161.26098379498299.4304048472265057.25280961497993.524010196
2264929.99574944497948.249863788
#Sta/Elev= 30
       0 2347.34     6.6 2344.73    15.2 2342.68    28.2  2341.2    77.9 2339.33
   116.4 2338.72   124.9 2338.21   133.3 2338.47     146 2337.99   213.9 2338.88
   222.1  2337.9   232.3 2334.09     239 2333.34   248.6 2334.24   255.9 2336.04
   268.5 2337.96   283.2    2338   302.3 2339.73   349.7  2339.6   361.8 2339.09
   368.1 2339.64   383.8 2339.94   392.2 2340.76   396.4 2341.69   407.7 2346.63
   413.4 2348.62   426.1 2351.24   434.6 2353.73   449.5 2360.12   458.2 2364.44
#Mann= 5 ,-1,0
       0     .05       0      70     .06       0     170      .1       0
   232.3    .045       0   248.6      .1       0
#XS Ineff= 2 , 0
          211.35 2344.51
Permanent Ineff=
       F       F
Bank Sta=232.3,248.6
XS Rating Curve= 0 ,0
Exp/Cntr(USF)=0,0
Exp/Cntr=0.3,0.1

Type RM Length L Ch R = 1 ,615     ,169.6,179.4,189.9
XS GIS Cut Line= 3
2265265.81299156498213.9125727422265235.90214409497998.418512511
2264964.25726564497855.254319814
#Sta/Elev= 30
       0 2346.22    37.1 2340.04    53.2 2338.83    77.5 2335.26   162.3 2333.96
   178.4 2333.08   221.8 2333.51   244.4 2334.57   280.6 2334.25   285.1 2333.66
   294.1 2330.46     300 2329.28   307.7 2328.86   314.6 2329.21   319.1 2330.47
   325.8  2334.8   327.8 2335.36   343.9 2337.18   357.5 2336.41   366.5  2337.4
   389.1 2335.83   429.8 2336.42   456.9 2336.11     475 2336.98   479.5 2337.86
     484 2339.55   494.8 2345.79   502.1 2351.07   514.4 2361.37   524.6 2368.66
#Mann= 5 ,-1,0
       0     .05       0      80     .06       0     180      .1       0
     300    .045       0   314.6      .1       0
#XS Ineff= 2 , 0
          272.46  2341.1
Permanent Ineff=
       F       F
Bank Sta=300,314.6
XS Rating Curve= 0 ,0
Exp/Cntr(USF)=0,0
Exp/Cntr=0.5,0.3

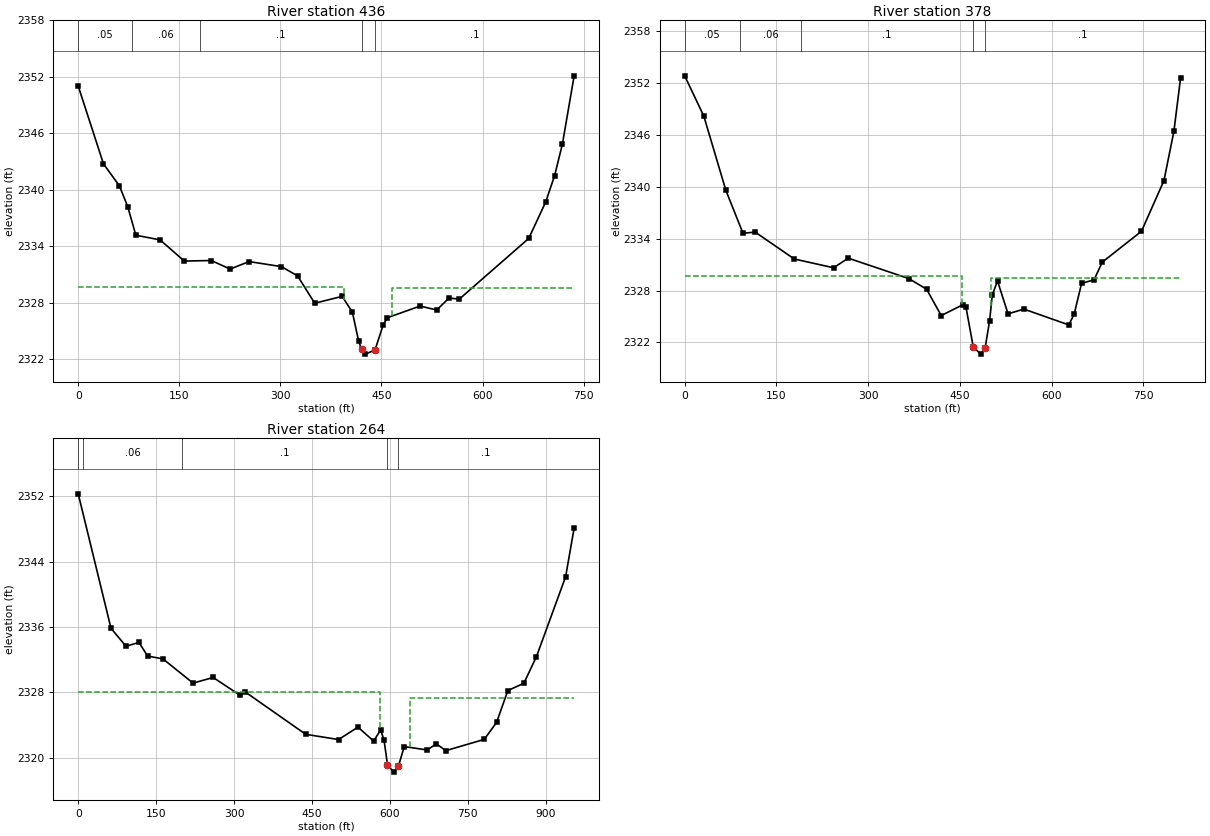
Type RM Length L Ch R = 1 ,436     ,57.9,57.9,57.1
XS GIS Cut Line= 4
2265277.50541376498218.6711166592265272.61091144497885.844959279
2265166.15548611497635.0017156662265038.89842593 497605.63470178
#Sta/Elev= 30
       0 2351.01    37.5 2342.74    61.1 2340.41    73.5 2338.19    85.5 2335.16
   121.5 2334.66   157.5 2332.41   197.5 2332.47   225.5 2331.56   253.5 2332.36
   301.5 2331.82   325.5 2330.84     351 2327.93   391.7 2328.66   406.9 2326.98
   416.1 2323.91  420.76 2323.03   426.1 2322.52   440.5 2322.96   452.7 2325.66
   458.8 2326.39   507.4 2327.63     532 2327.21   550.3 2328.48   565.6 2328.37
   668.6 2334.82   693.6 2338.66     707 2341.49   718.6 2344.86     736  2352.1
#Mann= 5 ,-1,0
       0     .05       0      80     .06       0     180      .1       0
  420.76    .045       0   440.5      .1       0
#XS Ineff= 2 , 0
             395  2329.7     465          2329.5
Permanent Ineff=
       F       F
Bank Sta=420.76,440.5
XS Rating Curve= 0 ,0
Exp/Cntr(USF)=0,0
Exp/Cntr=0.5,0.3

Type RM Length L Ch R = 1 ,378     ,114.8,114,111.9
XS GIS Cut Line= 4
 2265292.1889207498228.4601212882265301.97792533497828.334557085
2265215.10050925497611.7528296732265041.34567709497577.491313472
#Sta/Elev= 30
       0 2352.84    31.3 2348.18    67.3  2339.6    95.3 2334.63   115.3 2334.76
   179.3 2331.65   243.4 2330.64   267.4 2331.75   366.4 2329.39   395.4 2328.16
   419.4 2325.11   455.4 2326.39   459.7 2326.14   471.7 2321.49     484 2320.65
     491 2321.31   498.5 2324.52   502.8 2327.49   511.4 2329.11   528.6 2325.31
   554.5 2325.86   627.8 2324.03   636.6 2325.25   648.8 2328.84   669.2 2329.24
   682.6 2331.29   746.7 2334.86   783.4 2340.71   799.7 2346.41   810.7 2352.63
#Mann= 5 ,-1,0
       0     .05       0      90     .06       0     190      .1       0
   471.7    .045       0     491      .1       0
#XS Ineff= 2 , 0
             454  2329.7     501          2329.5
Permanent Ineff=
       F       F
Bank Sta=471.7,491
XS Rating Curve= 0 ,0
Exp/Cntr(USF)=0,0
Exp/Cntr=0.5,0.3

Type RM Length L Ch R = 1 ,264     ,,,
XS GIS Cut Line= 4
2265301.97792533498233.3546236022265425.56410877497812.427424563
2265278.72903934497546.9006740072265068.26543982497518.757285699
#Sta/Elev= 30
       0  2352.3    63.1 2335.83    92.1 2333.63   116.9 2334.11   133.6 2332.43
     163 2332.09   221.1 2329.12   259.7 2329.81   311.3 2327.64   321.2 2328.05
   437.9 2322.85     501 2322.21   538.4 2323.73   568.7 2322.02   582.1  2323.4
   588.7 2322.11   595.2 2319.15   606.9 2318.22   616.1 2318.91   627.5 2321.35
   671.7 2320.93   689.2 2321.69   707.5 2320.85   781.5 2322.23   805.2 2324.31
   826.9 2328.21   857.7  2329.1   881.9 2332.36   938.1 2342.15   954.5 2348.12
#Mann= 5 ,-1,0
       0     .05       0      10     .06       0     200      .1       0
   595.2    .045       0   616.1      .1       0
#XS Ineff= 2 , 0
          581.33 2328.07  638.55         2327.26
Permanent Ineff=
       F       F
Bank Sta=595.2,616.1
XS Rating Curve= 0 ,0
Exp/Cntr(USF)=0,0
Exp/Cntr=0.3,0.1
LCMann Table=0

Chan Stop Cuts=-1
Use User Specified Reach Order=0
Composite Channel Slope=5